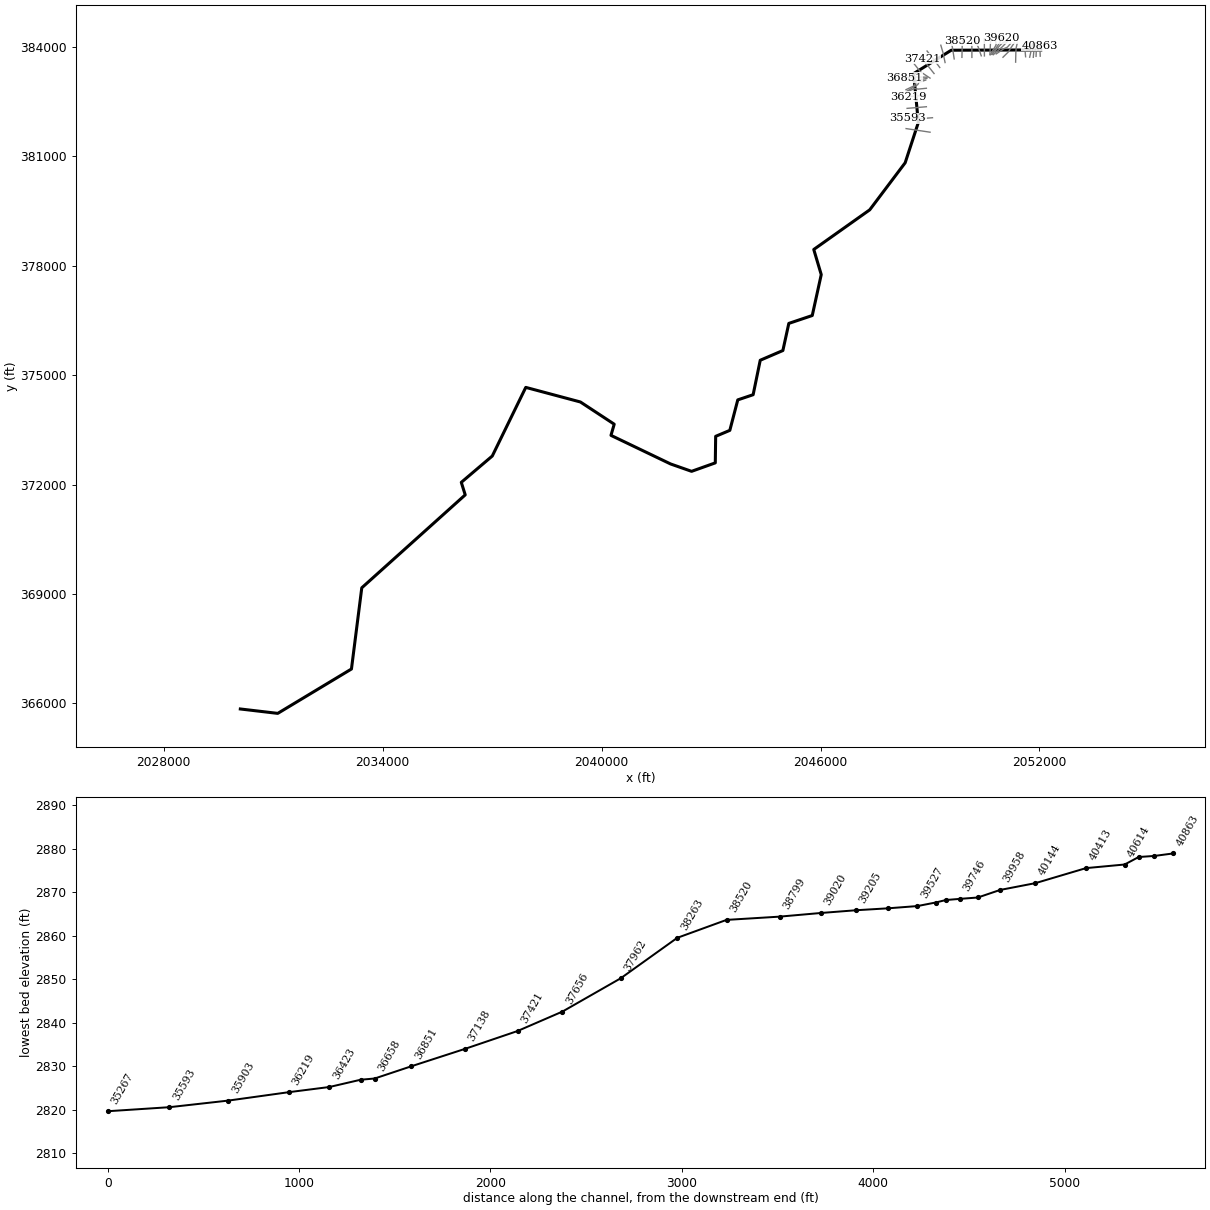
--- MEADOWCK2.prj (project) ---

Proj Title=MEADOWCK2
Current Plan=p01
Default Exp/Contr=0,0
English Units
Geom File=g01
Flow File=f01
Plan File=p01
Background Map Layer=DrainagePoints_filtd_shifted_3sigdig
BEGIN DESCRIPTION:
Stream Name- Meadow Creek 2
Flood Zone: Zone A
Greenbrier County, WV
County-Wide Study
WVDHSEM-2018-3, Flood Risk Project
HEC-RAS Version: 5.0.7
General Notes:
For the Hydrology Regression was used.
Upstream Extents: Approximately 960 feet upstream of Main Street
Downstream Extents: Approximately190 feet upstream of the confluence with Meadow River
END DESCRIPTION:
DSS Export Rating Curves= 0
DSS Export Rating Curve Sorted= 0
DSS Export Volume Flow Curves= 0
DXF Filename=..\..\..\..\..\fz_Working\Nov1\Models\MEADOWCK2\MEADOWCK.
DXF OffsetX= 0
DXF OffsetY= 0
DXF ScaleX= 0
DXF ScaleY= 0

--- MEADOWCK2.p01 (plan) ---

Plan Title=Floodplain
Program Version=5.07
Short Identifier=Floodplain
Geom File=g01
Flow File=f01
Subcritical Flow
K Sum by GR= 0
Std Step Tol= 0.01
Critical Tol= 0.01
Num of Std Step Trials= 20
Max Error Tol= 0.3
Flow Tol Ratio= 0.001
Split Flow NTrial= 30
Split Flow Tol= 0.02
Split Flow Ratio= 0.02
Log Output Level= 0
Friction Slope Method= 1
Unsteady Friction Slope Method= 2
Unsteady Bridges Friction Slope Method= 1
Parabolic Critical Depth
Global Vel Dist= 0 , 0 , 0
Global Log Level= 0
CheckData=False
Encroach Param=-1 ,0,0, 0
Mapping Interval=1HOUR
Computation Time Step Use Courant=        0
Computation Time Step Use Time Series=    0
Computation Time Step Count To Double=0
Computation Time Step Max Doubling=0
Computation Time Step Max Halving=0
Computation Time Step Residence Courant=0
Run HTab= 0
Run UNet= 0
Run Sediment= 0
Run PostProcess= 0
Run WQNet= 0
Run RASMapper= 0
UNET Theta= 0
UNET Theta Warmup= 0
UNET ZTol= 0
UNET ZSATol= 0
UNET MxIter= 0
UNET Max Iter WO Improvement= 0
UNET MaxInSteps= 0
UNET DtIC= 0
UNET DtMin= 0
UNET MaxCRTS= 0
UNET WFStab= 0
UNET SFStab= 0
UNET WFX= 1
UNET SFX= 1
UNET 1D Methodology=Finite Difference
UNET DSS MLevel= 1
UNET Pardiso=0
UNET DZMax Abort= 0
UNET Use Existing IB Tables= 0
UNET Froude Reduction=False
UNET Froude Limit= 0
UNET Froude Power= 0
UNET D1 Cores= 0
UNET D2 Coriolis=0
UNET D2 Cores= 0
UNET D2 Theta= 1
UNET D2 Theta Warmup= 1
UNET D2 Z Tol= 0.01
UNET D2 Volume Tol= 0.01
UNET D2 Max Iterations= 20
UNET D2 Equation= 0
UNET D2 RampUpFraction=0.1
UNET D2 TimeSlices= 1
UNET D2 BCVolumeCheck=0
UNET D1D2 MaxIter= 0
UNET D1D2 ZTol=0.01
UNET D1D2 QTol=0.1
UNET D1D2 MinQTol=1
Write IC File= 0
Write IC File at Fixed DateTime=0
Write IC File at Sim End=0
Echo Input=False
Echo Parameters=False
Echo Output=False
Write Detailed= 0
HDF Write Warmup=0
HDF Write Time Slices=0
HDF Flush=0
HDF Face Node Velocities=0
HDF Compression= 1
HDF Chunk Size= 1
HDF Spatial Parts= 1
HDF Use Max Rows=0
HDF Fixed Rows= 1
Calibration Method= 0
Calibration Iterations= 20
Calibration Max Change=0.05
Calibration Tolerance=0.2
Calibration Maximum=1.5
Calibration Minimum=0.5
Calibration Optimization Method= 1
WQ AD Non Conservative
WQ ULTIMATE=-1
WQ Max Comp Step=1HOUR
WQ Output Interval=15MIN
WQ Output Selected Increments= 0
WQ Output face flow=0
WQ Output face velocity=0
WQ Output face area=0
WQ Output face dispersion=0
WQ Output cell volume=0
WQ Output cell surface area=0
WQ Output cell continuity=0
WQ Output cumulative cell continuity=0
WQ Output face conc=0
WQ Output face dconc_dx=0
WQ Output face courant=0
WQ Output face peclet=0
WQ Output face adv mass=0
WQ Output face disp mass=0
WQ Output cell mass=0
WQ Output cell source sink temp=0
WQ Output nsm pathways=0
WQ Output nsm derived pathways=0
WQ Output MaxMinRange=-1
WQ Daily Max Min Mean=-1
WQ Daily Range=0
WQ Daily Time=0
WQ Create Restart=0
WQ Fixed Restart=0
WQ System Summary=0
WQ Write To DSS=0
WQ Use Fixed Temperature=0
Sorting and Armoring Iterations= 10
XS Update Threshold= 0.02
Bed Roughness Predictor= 0
Hydraulics Update Threshold= 0.02
Energy Slope Method= 1
Volume Change Method= 1
Sediment Retention Method= 0
XS Weighting Method= 0
Number of US Weighted Cross Sections= 1
Number of DS Weighted Cross Sections= 1
Upstream XS Weight=0
Main XS Weight=1
Downstream XS Weight=0
Number of DS XS's Weighted with US Boundary= 1
Upstream Boundary Weight= 1
Weight of XSs Associated with US Boundary= 0
Number of US XS's Weighted with DS Boundary= 1
Downstream Boundary Weight= 0.5
Weight of XSs Associated with DS Boundary= 0.5
Percentile Method= 0
Sediment Output Level= 3
Mass or Volume Output= 0
Output Increment Type= 1
Profile and TS Output Increment= 1
XS Output Flag= 0
XS Output Increment= 10
Write Gradation File= 0
Read Gradation Hotstart= 0
Write HDF5 File= 1
Write Binary Output= 1
Write DSS Sediment File= 0
SV Curve= 0
Specific Gage Flag= 0

--- MEADOWCK2.f01 (steady flow) ---

Flow Title=NFF Regression Equation
Program Version=5.07
Number of Profiles= 6
Profile Names=f1p,f10p,f4p,f2p,f02p,f1pplus
River Rch & RM=MEADOWCK2,Main            ,40863
     524     276     368     443     733     775
River Rch & RM=MEADOWCK2,Main            ,39205
     586     310     412     497     819     867
River Rch & RM=MEADOWCK2,Main            ,37421
     660     350     465     559     919     976
River Rch & RM=MEADOWCK2,Main            ,34810
     840     451     595     714    1170    1240
River Rch & RM=MEADOWCK2,Main            ,34495
     935     503     663     795    1290    1380
River Rch & RM=MEADOWCK2,Main            ,30281
    1080     584     768     919    1490    1600
River Rch & RM=MEADOWCK2,Main            ,27945
    1240     676     885    1060    1710    1830
River Rch & RM=MEADOWCK2,Main            ,21078
    1400     768    1000    1200    1930    2080
River Rch & RM=MEADOWCK2,Main            ,14460
    1690     928    1210    1440    2310    2490
River Rch & RM=MEADOWCK2,Main            ,12568
    1870    1040    1350    1600    2560    2770
River Rch & RM=MEADOWCK2,Main            ,5413
    2090    1160    1510    1790    2850    3090
Boundary for River Rch & Prof#=MEADOWCK2,Main            , 1
Up Type= 0
Dn Type= 3
Dn Slope=0.00185
DSS Import GetInterval= 0
DSS Import GetPeak= 0
DSS Import FillOption= 0

--- MEADOWCK2.g01 (geometry) ---

Geom Title=USGS 10m DEM
Program Version=5.07

River Reach=MEADOWCK2       ,Main
Reach XY= 30
    2052035.6301     383921.5264    2049583.0721383913.555400001
    2048552.4232     383272.3234    2048680.5857     381930.6515
    2048319.5911     380826.2818    2047348.8287379536.576400001
     2045815.063     378448.9154     2046020.082     377760.0021
    2045773.7401376638.076400001    2045131.4222      376421.855
    2044968.7126      375678.365    2044348.1461375411.428400001
    2044153.6673     374466.4603    2043732.8501374324.689400001
    2043514.6461373488.772399999    2043126.7481     373325.1733
    2043116.5711372597.226399999    2042466.8105     372365.2136
    2041891.2017     372567.5133    2040257.7251373351.545399999
    2040346.4063373658.099199999    2039420.3472     374266.8868
    2037922.8542374667.353499999    2037005.1687     372785.4256
    2036155.7306     372063.1205    2036263.5497     371719.7849
    2033428.6683369170.965399999    2033145.7745366944.434800001
    2031126.1129365727.6978999992030100.43180501365848.186496015

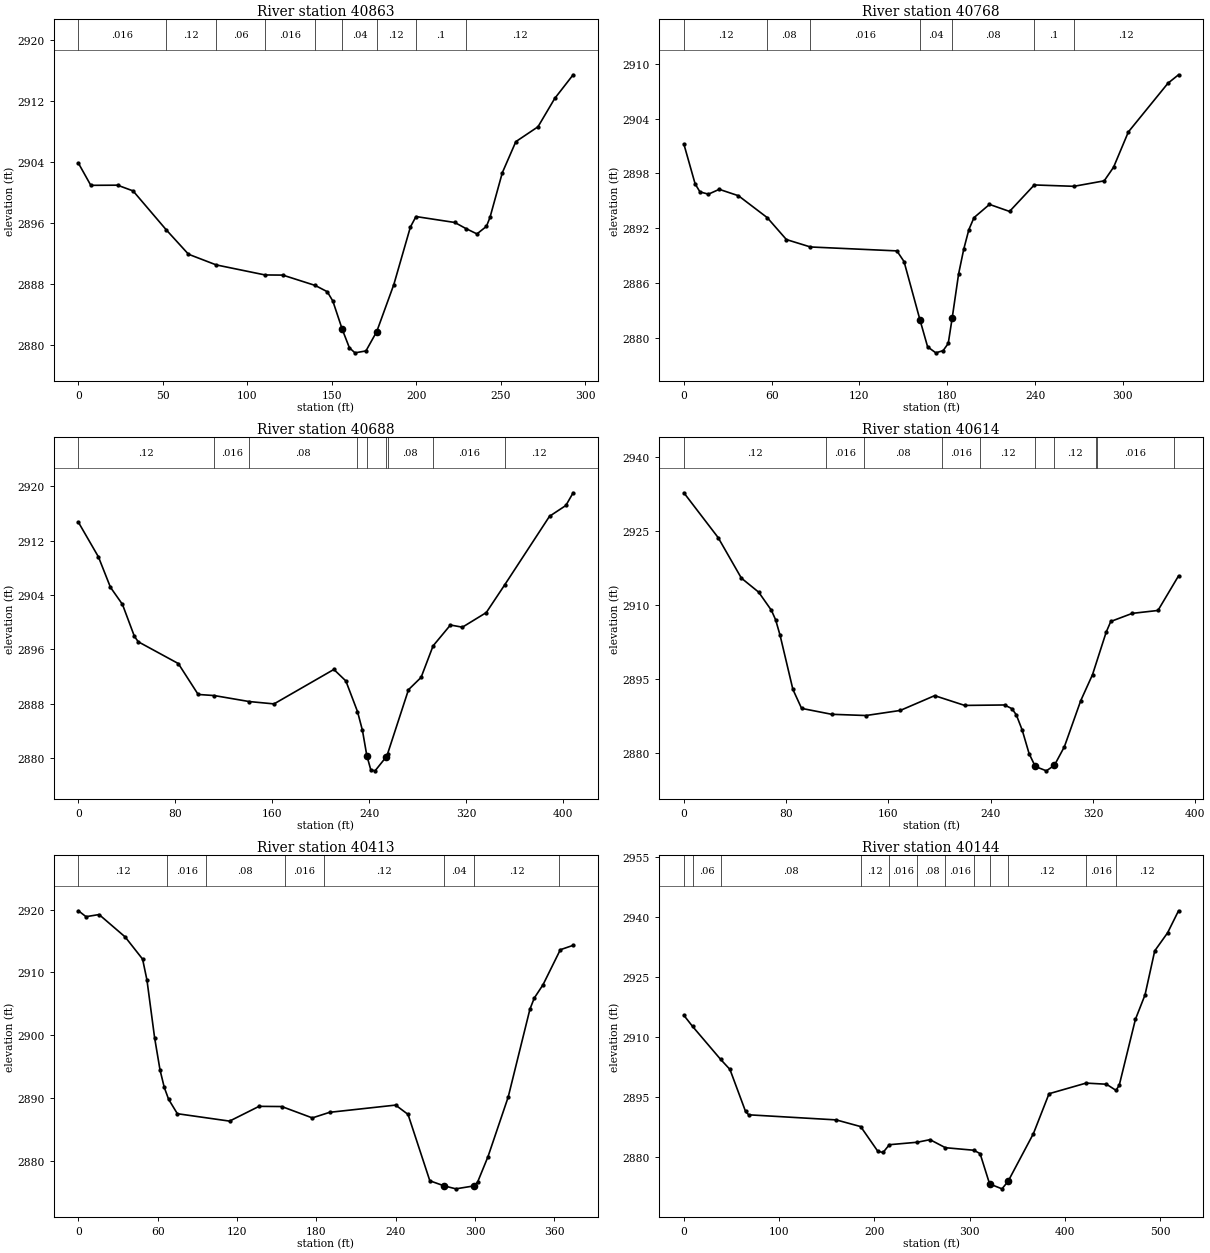
Type RM Length L Ch R = 1 ,40863   ,99.5,99.5,99.5
XS GIS Cut Line= 2
     2052021.308      383749.855     2052010.252      384042.334
#Sta/Elev= 30
       0 2903.84     7.3 2900.94    23.1 2900.96    32.3 2900.21      52 2895.08
    65.1 2891.89    81.5 2890.49   110.4 2889.17   120.9 2889.15   140.1 2887.79
   147.2 2886.97   150.5 2885.75   156.12882.016   160.3 2879.61   163.6 2878.94
   170.1 2879.19   176.52881.739   186.6 2887.91   196.4 2895.46   199.7 2896.84
   222.7 2896.06   229.2 2895.27   235.8 2894.56   241.4 2895.55   243.5 2896.73
   250.8  2902.6   258.8 2906.68   271.9 2908.63   281.8 2912.35   292.7 2915.46
#Mann= 9 ,-1 , 0
       0    .016       0      52     .12       0    81.5     .06       0
   110.4    .016       0   140.1     .12       0   156.1     .04       0
   176.5     .12       0   199.7      .1       0   229.2     .12       0
Bank Sta=156.1,176.5
XS Rating Curve= 0 ,0
Exp/Cntr=0.5,0.3

Type RM Length L Ch R = 1 ,40768   ,82.2,82.2,82.2
XS GIS Cut Line= 4
     2051906.728      383744.829     2051912.759      383893.582
     2051935.876      383951.877     2051967.033      384074.497
#Sta/Elev= 30
       0 2901.22     7.7 2896.86      11 2895.98    16.8 2895.73    24.2 2896.26
    37.3 2895.56      57 2893.16    70.1 2890.76    86.5 2889.95   145.6 2889.52
   150.5 2888.35   161.42881.957   166.6 2879.02   172.2 2878.36   177.2  2878.6
   180.7 2879.39   183.42882.175   187.8 2887.01   191.3 2889.71   194.8 2891.85
   198.3 2893.16   208.9 2894.61   222.6 2893.84   239.5 2896.74   266.6 2896.59
   287.3 2897.19   293.7 2898.68   303.8 2902.54   330.9 2907.88   338.1  2908.8
#Mann= 7 ,-1 , 0
       0     .12       0      57     .08       0    86.5    .016       0
   161.4     .04       0   183.4     .08       0   239.5      .1       0
   266.6     .12       0
Bank Sta=161.4,183.4
XS Rating Curve= 0 ,0
Exp/Cntr=0.5,0.3

Type RM Length L Ch R = 1 ,40688   ,73.3,73.3,73.3
XS GIS Cut Line= 4
     2051831.347      383719.702     2051850.444      383940.821
     2051877.581      384023.238     2051882.606      384122.741
#Sta/Elev= 30
       0 2914.68    16.5 2909.59    26.4 2905.12    36.3 2902.61    46.2 2897.89
    49.4  2897.1    82.4  2893.9    98.8 2889.35     112 2889.19   140.8 2888.31
   161.4 2887.96   210.8 2893.03   220.7 2891.34   230.3 2886.84   234.4 2884.06
     238 2880.36   241.3 2878.25   244.8 2878.11   254.12880.181   255.2 2880.64
   272.4 2890.05   282.8 2891.86   292.7  2896.5     307 2899.57   316.9 2899.25
   336.6  2901.4     352 2905.53   388.8 2915.57   402.3 2917.16   408.3 2919.03
#Mann= 9 ,-1 , 0
       0     .12       0     112    .016       0   140.8     .08       0
   230.3     .12       0     238     .04       0   254.1     .12       0
   255.2     .08       0   292.7    .016       0     352     .12       0
Bank Sta=238,254.1
XS Rating Curve= 0 ,0
Exp/Cntr=0.5,0.3

Type RM Length L Ch R = 1 ,40614   ,201.9,201.9,201.9
XS GIS Cut Line= 2
     2051731.844      383721.713     2051815.266      384099.624
#Sta/Elev= 30
       0 2932.79    26.8 2923.71      45 2915.48    58.5 2912.64    68.5 2908.95
    71.8 2907.02    75.3 2903.86    85.3 2892.91    92.1 2889.06   115.6 2887.86
   142.5 2887.61   169.3 2888.64   196.2 2891.64   219.7 2889.66   250.9 2889.75
   256.7 2888.99   260.1 2887.74   264.7 2884.66   270.1 2879.88   274.92877.284
   283.6 2876.39   289.92877.517   297.7 2881.28   310.5 2890.63   319.7  2895.9
   330.4 2904.52     334 2906.69   350.8 2908.33   370.9 2908.92     387 2915.93
#Mann= 10 ,-1 , 0
       0     .12       0  110.93    .016       0  141.18     .08       0
  201.68    .016       0  231.93     .12       0   274.9     .04       0
   289.9     .12       0  322.67     .08       0   323.3    .016       0
  383.17     .12       0
Bank Sta=274.9,289.9
XS Rating Curve= 0 ,0
Exp/Cntr=0.3,0.1

Type RM Length L Ch R = 1 ,40413   ,264.2,264.2,264.2
XS GIS Cut Line= 2
     2051620.279      383733.774     2051589.122       384106.66
#Sta/Elev= 30
       0 2919.82     5.7 2918.88    15.6 2919.22    35.3 2915.66    48.5 2912.13
    51.8 2908.81    57.6 2899.61    61.7 2894.48    64.9 2891.71    68.2 2889.81
    74.8 2887.52   114.3 2886.34   136.6 2888.69   153.8 2888.66   176.9 2886.85
     190 2887.74   239.9 2888.89   249.3 2887.41   265.8 2876.84   276.62876.032
   285.5 2875.56   299.42876.035     302 2876.67   309.8 2880.69   325.1 2890.19
   341.5 2904.15   344.8 2905.93   351.4 2908.04   364.5 2913.62   374.2 2914.32
#Mann= 8 ,-1 , 0
       0     .12       0   66.96    .016       0    96.6     .08       0
  155.88    .016       0  185.52     .12       0   276.6     .04       0
   299.4     .12       0  363.36    .016       0
Bank Sta=276.6,299.4
XS Rating Curve= 0 ,0
Exp/Cntr=0.3,0.1

Type RM Length L Ch R = 1 ,40144   ,184.8,184.8,184.8
XS GIS Cut Line= 4
     2051346.896      383586.026     2051352.927      383852.373
     2051362.978      383987.055      2051391.12      384101.634
#Sta/Elev= 30
       0  2915.4     9.2 2912.62    38.6 2904.41    48.4  2901.9    64.8 2891.41
    68.1 2890.58     160 2889.31   185.7 2887.64   203.7 2881.48   209.2 2881.18
   215.8 2883.12   245.3 2883.74   258.5 2884.38   274.7 2882.37   304.5 2881.74
   311.1  2880.9   321.12873.335   334.1 2872.11   340.52873.985   367.1 2885.89
   383.5 2895.84   422.4 2898.49   443.8 2898.21   453.9 2896.67   457.3 2898.02
   474.2 2914.38   484.3 2920.49   494.5 2931.48     508 2935.98   519.5 2941.48
#Mann= 12 ,-1 , 0
       0     .12       0     9.2     .06       0    38.6     .08       0
   185.7     .12       0   215.8    .016       0   245.3     .08       0
   274.7    .016       0   304.5     .12       0   321.1     .04       0
   340.5     .12       0   422.4    .016       0   453.9     .12       0
Bank Sta=321.1,340.5
XS Rating Curve= 0 ,0
Exp/Cntr=0.5,0.3

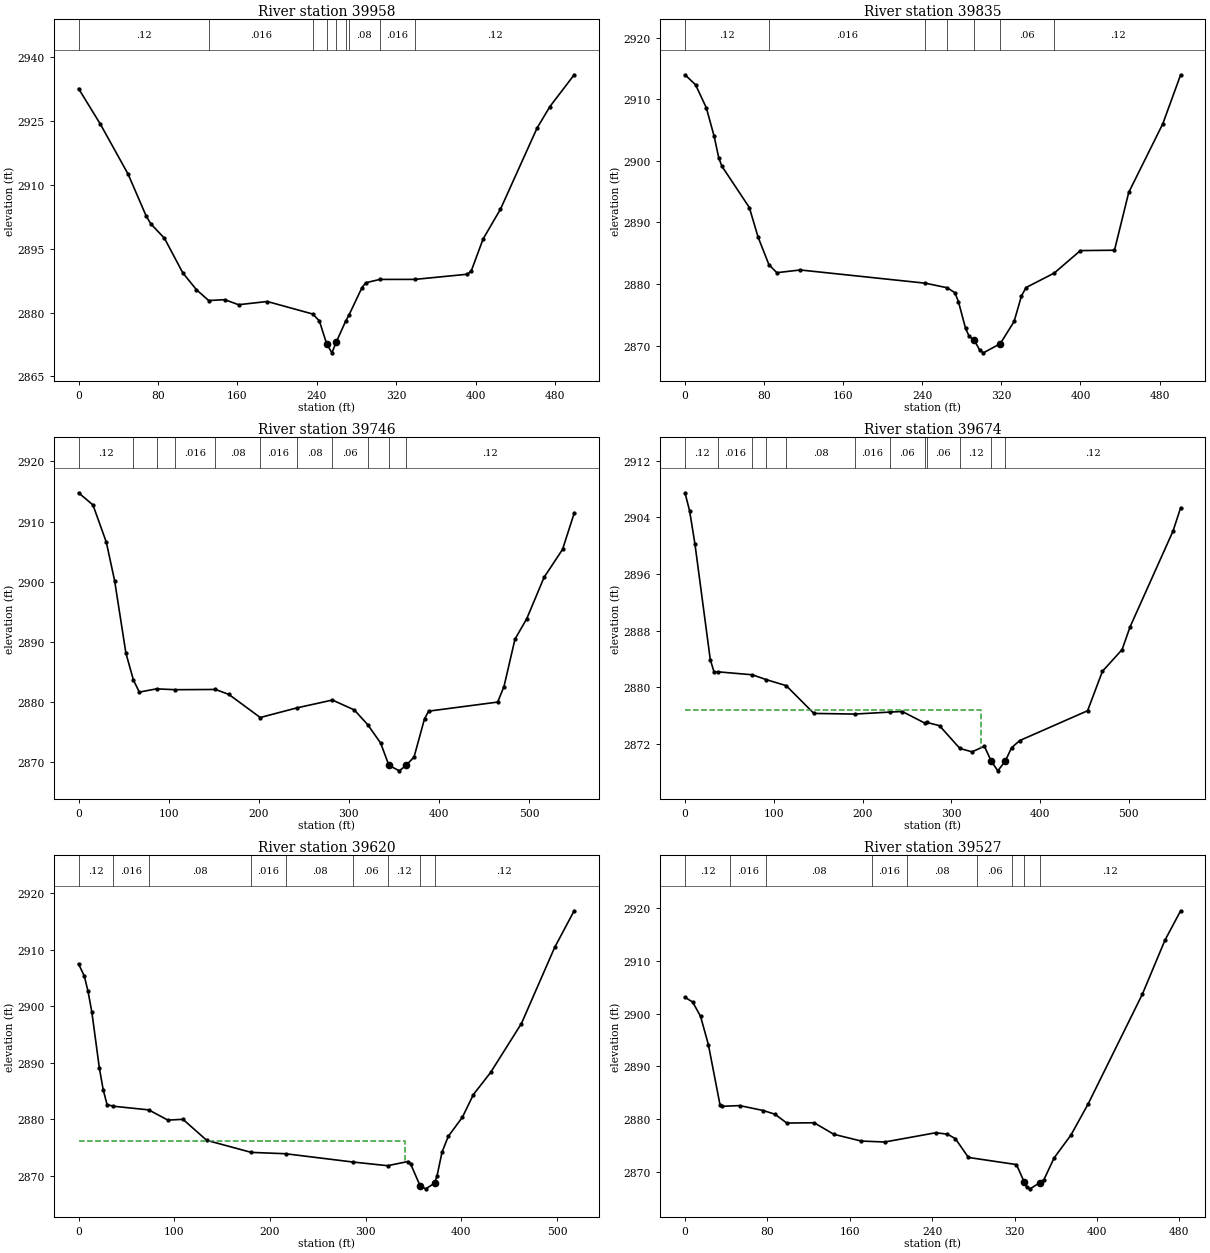
Type RM Length L Ch R = 1 ,39958   ,116,116,116
XS GIS Cut Line= 4
     2051000.142      383720.707     2051152.915       383871.47
     2051194.124      383943.836     2051306.693       384110.68
#Sta/Elev= 30
       0 2932.54      22 2924.19      50 2912.43    68.1 2902.66    72.8  2900.8
    86.6  2897.4     105 2889.31   118.8 2885.34   131.1 2882.81   147.3 2883.01
   161.2 2881.83   190.1 2882.58     236 2879.64   242.6 2878.02   249.92872.663
   255.2 2870.54   259.52873.014   269.1    2878   272.3 2879.36   285.5 2885.84
   289.2 2886.97   303.5 2887.76   338.9 2887.77   391.7 2888.98   395.6 2889.77
   407.5 2897.26     425 2904.25   461.8 2923.25   474.8 2928.31   499.2 2935.76
#Mann= 9 ,-1 , 0
       0     .12       0   131.1    .016       0     236     .12       0
   249.9     .04       0   259.5     .12       0   269.1    .016       0
   272.3     .08       0   303.5    .016       0   338.9     .12       0
Bank Sta=249.9,259.5
XS Rating Curve= 0 ,0
Exp/Cntr=0.5,0.3

Type RM Length L Ch R = 1 ,39835   ,94.4,94.4,94.4
XS GIS Cut Line= 4
     2050814.202       383812.17     2051024.264      383953.887
     2051119.747      383997.106      2051215.23      384103.645
#Sta/Elev= 30
       0 2914.01    10.7 2912.39    21.6 2908.64    29.5 2904.01    34.2 2900.48
    37.4 2899.13    65.1 2892.43    73.9 2887.64    84.9 2883.14    92.9 2881.84
   116.6 2882.28   243.2 2880.13   265.2 2879.39     273 2878.58   276.6 2877.12
   283.8 2872.77   287.4 2871.51   292.72870.849   298.2 2869.21   301.8 2868.81
   318.9  2870.3   332.9 2873.92   340.3 2878.05     345 2879.43   373.5 2881.78
   399.9 2885.43   434.4 2885.49   448.8 2894.89   483.2 2906.02   501.3    2914
#Mann= 7 ,-1 , 0
       0     .12       0    84.9    .016       0   243.2     .06       0
   265.2     .12       0   292.7     .04       0   318.9     .06       0
   373.5     .12       0
Bank Sta=292.7,318.9
XS Rating Curve= 0 ,0
Exp/Cntr=0.5,0.3

Type RM Length L Ch R = 1 ,39746   ,72.5,72.5,72.5
XS GIS Cut Line= 4
       2050734.8      383790.058      2050974.01      384000.121
       2051031.3      384058.416     2051133.819       384167.97
#Sta/Elev= 30
       0 2914.79      16 2912.77    30.8 2906.59    40.1 2900.13    52.6 2888.09
      61 2883.58    67.5  2881.6    86.6 2882.14   107.5    2882     152 2882.04
   166.9 2881.21   201.7 2877.37   242.3 2878.97   281.8 2880.28   306.1 2878.63
   320.9 2876.19   335.3 2873.12   344.5  2869.4   356.1 2868.49   363.82869.442
   372.4 2870.79     384 2877.15   388.6 2878.43   465.2 2879.94   472.2 2882.52
   484.4 2890.41   497.5 2893.83   516.7 2900.71   537.2 2905.36   550.1 2911.38
#Mann= 11 ,-1 , 0
       0     .12       0      61    .016       0    86.6     .12       0
   107.5    .016       0     152     .08       0   201.7    .016       0
   242.3     .08       0   281.8     .06       0   320.9     .12       0
   344.5     .04       0   363.8     .12       0
Bank Sta=344.5,363.8
XS Rating Curve= 0 ,0
Exp/Cntr=0.5,0.3

Type RM Length L Ch R = 1 ,39674   ,54.3,54.3,54.3
XS GIS Cut Line= 4
     2050708.668      383803.124      2050908.68      384036.304
     2050963.959      384092.589     2051111.707      384181.036
#Sta/Elev= 30
       0 2907.46     5.2 2904.92    11.2 2900.26    28.5 2883.92    32.8 2882.16
    37.1  2882.2      76 2881.78    91.2 2881.11     114 2880.25   145.2 2876.33
   191.3 2876.24   230.8 2876.52   244.8  2876.6   270.2 2874.96   272.4 2875.06
   286.7  2874.6   309.6 2871.39   323.4 2870.91   337.2  2871.7   345.12869.572
   352.4 2868.23   360.92869.634   367.9  2871.5   377.2 2872.51   453.5 2876.71
   470.2 2882.27   492.4 2885.34   501.3 2888.53   549.8 2902.08   558.3 2905.35
#Mann= 12 ,-1 , 0
       0     .12       0    37.1    .016       0      76     .08       0
    91.2    .016       0     114     .08       0   191.3    .016       0
   230.8     .06       0   270.2     .08       0   272.4     .06       0
   309.6     .12       0   345.1     .04       0   360.9     .12       0
#XS Ineff= 2 , 0
          332.89 2876.88
Permanent Ineff=
       F       F
Bank Sta=345.1,360.9
XS Rating Curve= 0 ,0
Exp/Cntr=0.5,0.3

Type RM Length L Ch R = 1 ,39620   ,94.7,94.7,94.7
XS GIS Cut Line= 4
     2050693.592      383800.109     2050881.542      384076.507
     2050917.725      384131.787     2050964.964      384239.331
#Sta/Elev= 30
       0 2907.52       6 2905.37     9.9 2902.68    13.9 2899.01    21.8 2889.02
    25.8 2885.21    29.8 2882.59    36.3 2882.29    73.4 2881.64    93.3 2879.83
   109.1 2879.97     134 2876.24   180.5 2874.11   216.3 2873.87   287.2 2872.39
   322.9 2871.75   344.2 2872.49     347 2872.04     3572868.132   362.7 2867.65
     3722868.656   374.5 2869.91   379.7 2874.11   386.2 2876.93   401.1 2880.36
   412.5 2884.35   430.5 2888.27   462.7 2896.94   497.4 2910.42   517.8 2916.92
#Mann= 9 ,-1 , 0
       0     .12       0    36.3    .016       0    73.4     .08       0
   180.5    .016       0   216.3     .08       0   287.2     .06       0
   322.9     .12       0     357     .04       0     372     .12       0
#XS Ineff= 2 , 0
          341.53 2876.12
Permanent Ineff=
       F       F
Bank Sta=357,372
XS Rating Curve= 0 ,0
Exp/Cntr=0.5,0.3

Type RM Length L Ch R = 1 ,39527   ,154.1,154.1,154.1
XS GIS Cut Line= 4
     2050655.398      383792.068     2050813.197      384060.426
     2050803.146      384119.726      2050796.11       384229.28
#Sta/Elev= 30
       0 2903.08     7.5 2902.18    15.1 2899.48    22.7 2894.14    34.1 2882.64
    35.5 2882.45    53.1 2882.59      76 2881.66    87.4 2880.95    98.8 2879.29
   125.4 2879.34   144.5 2877.16   171.1 2875.88   193.9  2875.7   243.4 2877.45
   254.8 2877.19   262.5 2876.33   275.2 2872.78   321.8 2871.43   329.5 2868.07
   331.8 2867.12   335.1 2866.84   344.52868.007   348.5 2868.59   358.4  2872.7
   374.7 2877.01   391.5 2882.94   444.1 2903.69     466 2913.89   481.2 2919.45
#Mann= 9 ,-1 , 0
       0     .12       0   44.04    .016       0    78.3     .08       0
   181.1    .016       0  215.36     .08       0  283.89     .06       0
   317.3     .12       0   329.5     .04       0   344.5     .12       0
Bank Sta=329.5,344.5
XS Rating Curve= 0 ,0
Exp/Cntr=0.3,0.1

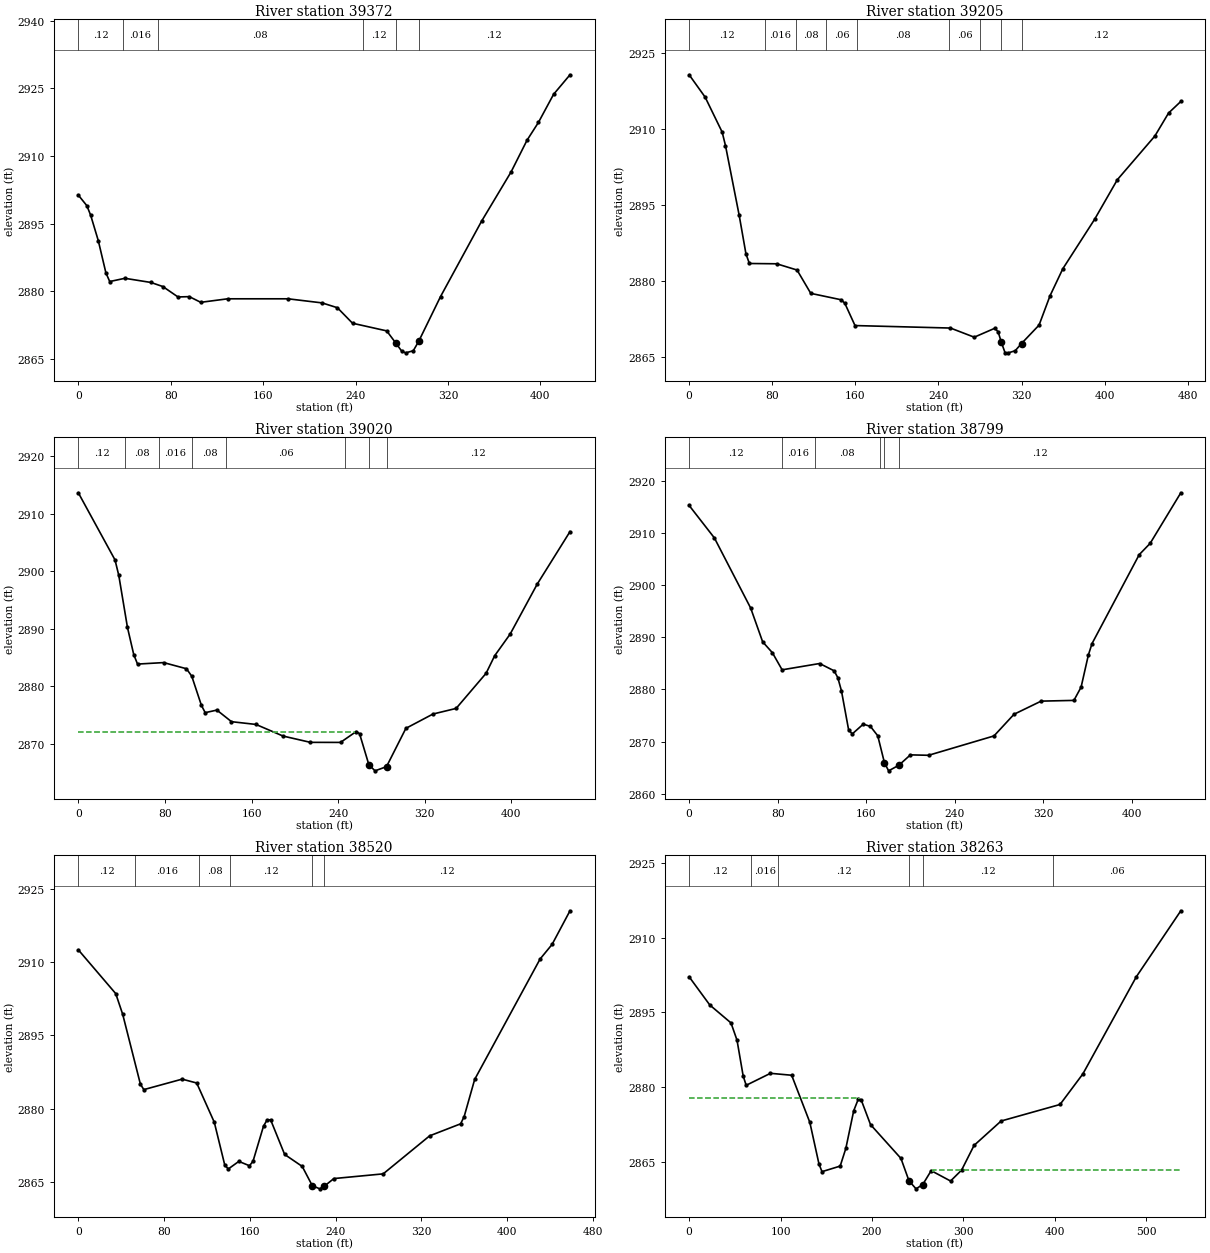
Type RM Length L Ch R = 1 ,39372   ,166.3,166.3,166.3
XS GIS Cut Line= 2
     2050641.327      383791.063     2050663.439      384216.214
#Sta/Elev= 30
       0 2901.32     7.4 2898.97    10.7 2896.85    17.3 2891.21    23.9 2884.05
    27.2 2882.14    40.3 2882.86    62.8 2881.94    73.2 2881.03    86.3 2878.72
    96.1 2878.79     106 2877.53   129.3 2878.31   181.6 2878.31   211.1  2877.4
   224.3 2876.33   237.4 2872.89     267 2871.19   274.92868.483   280.1 2866.66
   283.4 2866.32     290 2866.78   294.72868.873   313.6  2878.8   349.1 2895.51
   374.7 2906.47   388.5  2913.5   398.4 2917.46   411.5 2923.69   425.7 2928.02
#Mann= 6 ,-1 , 0
       0     .12       0   39.02    .016       0    68.6     .08       0
  246.06     .12       0   274.9     .04       0   294.7     .12       0
Bank Sta=274.9,294.7
XS Rating Curve= 0 ,0
Exp/Cntr=0.3,0.1

Type RM Length L Ch R = 1 ,39205   ,183.9,183.9,183.9
XS GIS Cut Line= 2
      2050491.57       383756.89      2050489.56      384230.285
#Sta/Elev= 30
       0 2920.62    15.4 2916.22    31.8 2909.33      35 2906.67    48.2 2892.93
    54.7 2885.36      58 2883.47    84.3 2883.41   103.9 2882.18   117.1 2877.59
   146.5 2876.32   149.9 2875.63   159.7 2871.25   251.6 2870.76   274.5 2868.96
   294.2 2870.71   297.5 2870.03   300.42868.078   304.1 2865.93   307.4 2865.88
   313.9 2866.29     3202867.713   336.9 2871.34   347.5 2877.13   359.8 2882.44
   390.4 2892.17   412.3 2899.97   448.4 2908.56   461.6 2913.09   473.4 2915.37
#Mann= 9 ,-1 , 0
       0     .12       0   73.14    .016       0  102.68     .08       0
  132.21     .06       0  161.75     .08       0  250.36     .06       0
   279.9     .12       0   300.4     .04       0     320     .12       0
Bank Sta=300.4,320
XS Rating Curve= 0 ,0
Exp/Cntr=0.3,0.1

Type RM Length L Ch R = 1 ,39020   ,215.7,215.7,215.7
XS GIS Cut Line= 3
     2050405.132      383759.906     2050323.721      383995.095
     2050243.314      384184.051
#Sta/Elev= 30
       0 2913.67    33.9 2901.98    37.4 2899.27    45.4 2890.22    51.2  2885.5
    54.7 2883.84    78.8  2884.1    99.9 2883.03   104.8 2881.73   113.7 2876.66
   117.2 2875.38     128 2875.83   141.5 2873.81   164.1 2873.33   189.1 2871.31
   214.4 2870.21   242.2  2870.2   256.7 2872.09   259.8 2871.72   268.42866.312
   274.1 2865.25   284.72865.983   302.6 2872.65   327.6 2875.14     349 2876.12
   376.7 2882.24   384.6 2885.29   398.9 2889.06   423.9 2897.76   454.2 2906.91
#Mann= 8 ,-1 , 0
       0     .12       0   42.95     .08       0    74.2    .016       0
  105.46     .08       0  136.72     .06       0  245.93     .12       0
   268.4     .04       0   284.7     .12       0
#XS Ineff= 2 , 0
          255.79 2871.98
Permanent Ineff=
       F       F
Bank Sta=268.4,284.7
XS Rating Curve= 0 ,0
Exp/Cntr=0.3,0.1

Type RM Length L Ch R = 1 ,38799   ,277.6,277.6,277.6
XS GIS Cut Line= 2
     2050148.836      383716.687     2050147.831      384160.934
#Sta/Elev= 30
       0 2915.27    22.8 2909.05    55.6  2895.6    66.4 2889.14    75.2 2887.05
      84 2883.77   117.9 2884.98     131 2883.58   134.3 2882.27   137.6 2879.74
   144.1 2872.24   147.4 2871.49   157.3 2873.36   163.8 2872.92   170.4 2871.13
   176.42865.986   180.2 2864.41   189.52865.489   199.9 2867.47   216.3 2867.39
   275.4  2871.1   293.5 2875.25     318 2877.77   347.6 2877.91   354.1 2880.45
   360.7 2886.64     364 2888.81   406.6 2905.84   416.5 2908.01   444.2  2917.7
#Mann= 6 ,-1 , 0
       0     .12       0    83.8    .016       0  113.34     .08       0
  172.41     .12       0   176.4     .04       0   189.5     .12       0
Bank Sta=176.4,189.5
XS Rating Curve= 0 ,0
Exp/Cntr=0.3,0.1

Type RM Length L Ch R = 1 ,38520   ,257.3,257.3,257.3
XS GIS Cut Line= 2
     2049875.453      383717.692     2049886.509      384176.011
#Sta/Elev= 30
       0 2912.51    34.9 2903.56    41.4 2899.32    57.9 2885.05    61.1 2883.94
    96.8 2886.08   110.4 2885.29   126.8 2877.27   136.6 2868.49   139.9 2867.73
   149.7 2869.27   159.6 2868.38   162.9 2869.29   172.7 2876.48     176 2877.73
   179.3 2877.78   192.4 2870.69   208.8 2868.24   218.22864.304   225.2 2863.66
   229.22864.172   238.3 2865.76   284.3 2866.72   327.6 2874.49   356.5 2876.95
   359.8 2878.43   369.6 2886.02   430.6 2910.63   441.8 2913.62   458.5 2920.49
#Mann= 6 ,-1 , 0
       0     .12       0   53.27    .016       0  112.36     .08       0
  141.91     .12       0   218.2     .04       0   229.2     .12       0
#XS Ineff= 2 , 0
             175  2877.1
Permanent Ineff=
       F       F
Bank Sta=218.2,229.2
XS Rating Curve= 0 ,0
Exp/Cntr=0.3,0.1

Type RM Length L Ch R = 1 ,38263   ,295.6,295.6,295.6
XS GIS Cut Line= 4
      2049663.38      383674.474     2049631.218      383884.536
     2049610.111      384014.192     2049550.811      384199.128
#Sta/Elev= 30
       0 2902.12    22.6 2896.46    45.8 2892.86    52.4 2889.39    59.1 2882.24
    62.4 2880.33      89 2882.74   112.2 2882.35   132.1 2872.88   142.1 2864.52
   145.4 2862.99   165.3 2864.11   171.5 2867.67   180.1 2875.22   185.2  2877.6
   188.5  2877.3   198.5 2872.44   231.8 2865.65   240.6 2861.15   248.3 2859.54
   255.62860.392   264.9 2863.19   286.1 2861.11   298.2 2863.31   311.8 2868.26
   341.4 2873.16   405.9 2876.48   430.9 2882.62   489.4 2902.13   538.1 2915.38
#Mann= 6 ,-1 , 0
       0     .12       0   67.72    .016       0    97.6     .12       0
   240.6     .04       0   255.6     .12       0  398.61     .06       0
#XS Ineff= 2 , 0
          185.87 2877.88  266.93         2863.28
Permanent Ineff=
       F       F
Bank Sta=240.6,255.6
XS Rating Curve= 0 ,0
Exp/Cntr=0.3,0.1

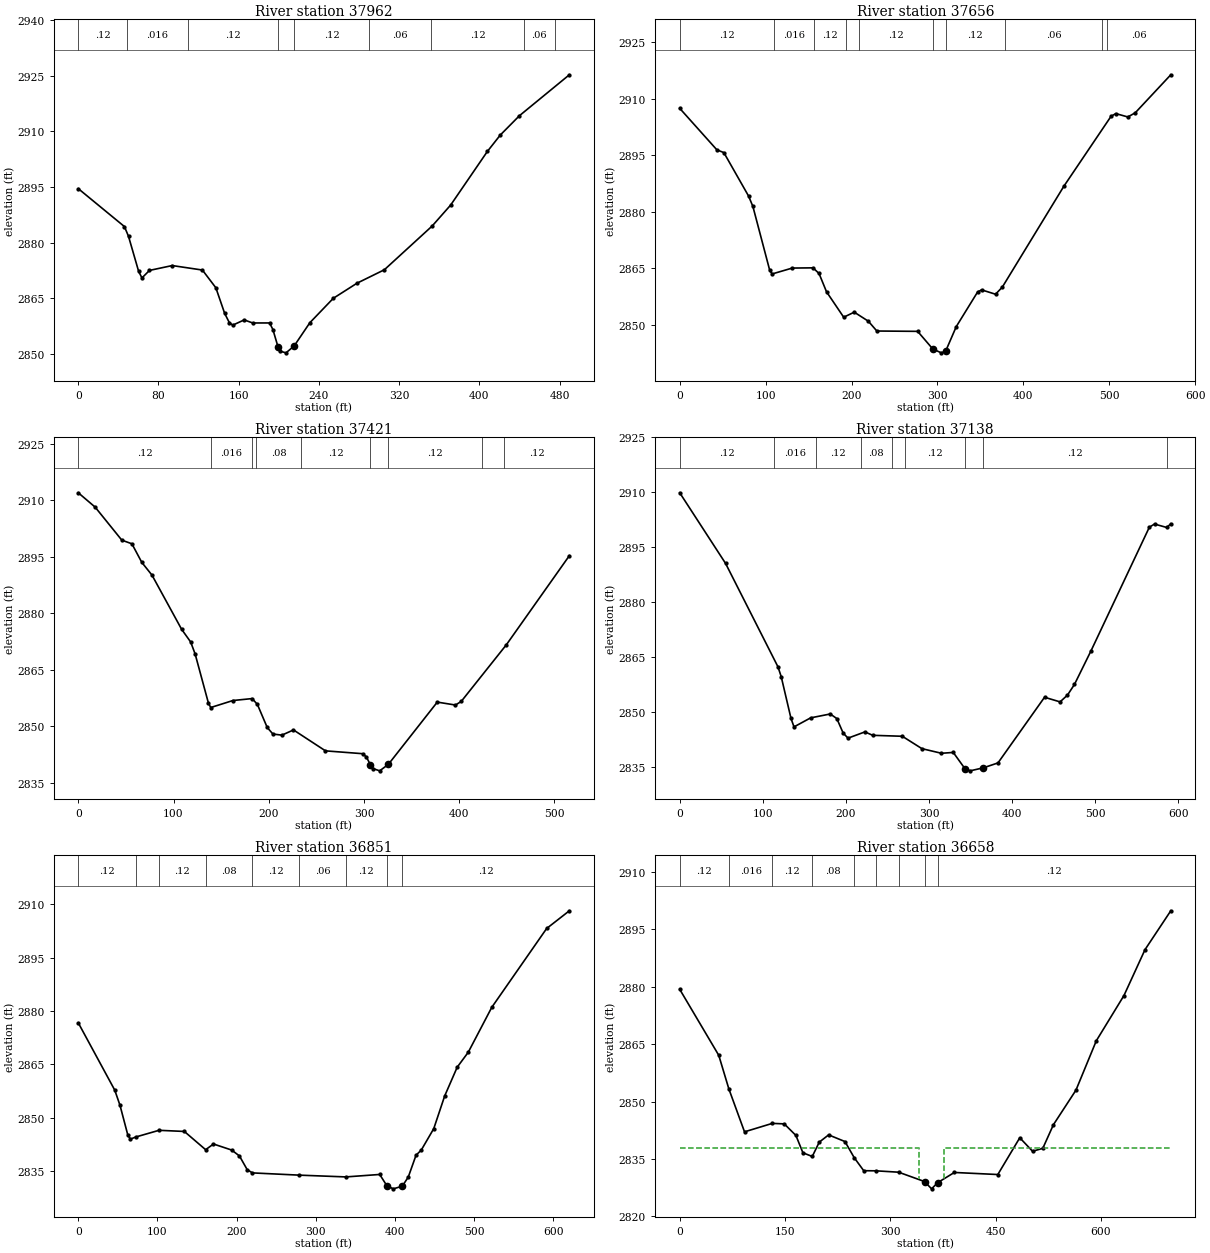
Type RM Length L Ch R = 1 ,37962   ,304.5,304.5,304.5
XS GIS Cut Line= 3
     2049413.474      383575.516     2049358.877      383841.057
     2049296.835       384050.76
#Sta/Elev= 30
       0 2894.56      46 2884.33    50.1 2881.69    60.2 2872.23    63.5 2870.46
      71 2872.49    93.7  2873.8   123.8 2872.59   137.2 2867.81     146 2860.89
   150.6 2858.42     154 2857.71   165.5 2859.13     174  2858.3   190.8 2858.31
   194.1 2856.54   199.2 2851.86   200.8 2850.72   207.2 2850.24   215.32852.092
     231 2858.38   254.4 2864.97     278 2869.04   305.3 2872.67   352.9 2884.46
   371.4 2890.13     408  2904.6   420.9 2909.03     440 2914.25   489.8  2925.3
#Mann= 9 ,-1 , 0
       0     .12       0   48.74    .016       0  109.05     .12       0
   199.2     .04       0   215.3     .12       0  290.39     .06       0
  351.99     .12       0   444.4     .06       0   475.2     .12       0
Bank Sta=199.2,215.3
XS Rating Curve= 0 ,0
Exp/Cntr=0.3,0.1

Type RM Length L Ch R = 1 ,37656   ,234.7,234.7,234.7
XS GIS Cut Line= 3
     2049268.295      383439.023     2049049.907      383730.622
     2048919.618      383891.932
#Sta/Elev= 30
       0 2907.46    43.3 2896.44    51.4 2895.71    80.2 2884.17    85.2 2881.42
   104.8 2864.47   107.6 2863.52     131 2865.08   155.2 2865.14   162.2 2863.64
   170.9 2858.79   190.9 2852.04   203.2 2853.38   219.6 2850.98   229.5 2848.38
     277 2848.29   294.62843.619   304.5 2842.59   309.62843.036     322 2849.57
   346.7  2858.7   351.4  2859.3   367.7 2858.14   375.6 2860.04   447.3 2886.82
   502.2 2905.36   507.7 2906.06   521.7 2905.17   530.3 2906.27   571.7 2916.36
#Mann= 10 ,-1 , 0
       0     .12       0  110.12    .016       0  156.37     .12       0
  193.27     .08       0  208.66     .12       0   294.6     .04       0
   309.6     .12       0  378.17     .06       0  492.08     .12       0
  497.87     .06       0
Bank Sta=294.6,309.6
XS Rating Curve= 0 ,0
Exp/Cntr=0.3,0.1

Type RM Length L Ch R = 1 ,37421   ,275.9,275.9,275.9
XS GIS Cut Line= 2
     2049111.949      383273.991      2048790.57      383677.265
#Sta/Elev= 30
       0 2912.03    17.7 2908.22    45.7 2899.44    56.3 2898.47    66.7 2893.53
    77.4 2890.14   108.5 2875.75     118 2872.38   122.7 2869.19   136.7  2856.1
   139.1 2854.95   162.4 2856.81   182.6 2857.33   188.1 2855.77   198.4 2849.65
   204.4  2847.9   213.8 2847.61     226 2848.99   259.6 2843.43   298.5 2842.68
   302.5 2841.82   306.82839.737   309.5 2838.73   316.5 2838.12   325.62839.836
     377 2856.39   396.1 2855.61   402.2 2856.58   449.6 2871.65   515.7 2895.31
#Mann= 9 ,-1 , 0
       0     .12       0  139.41    .016       0  182.22     .12       0
   186.8     .08       0   234.2     .12       0   306.8     .04       0
   325.6     .12       0  423.78     .06       0   446.6     .12       0
Bank Sta=306.8,325.6
XS Rating Curve= 0 ,0
Exp/Cntr=0.3,0.1

Type RM Length L Ch R = 1 ,37138   ,278.4,278.4,278.4
XS GIS Cut Line= 3
     2049001.514      383148.666     2048737.214      383323.625
     2048567.218      383538.291
#Sta/Elev= 30
       0 2909.85    55.2 2890.57   118.2 2862.37   122.1  2859.7   133.9 2848.28
   137.5 2845.99   157.5 2848.45   181.1 2849.51     189 2848.26   196.7 2844.28
   202.5 2842.92   222.8 2844.62   232.2 2843.69   267.8 2843.43   291.4 2840.05
   314.9 2838.79   329.1 2839.02     3432834.638   349.4    2834   365.42834.833
   382.9 2836.16   438.9 2854.07   457.6 2852.81   466.5 2854.66   474.9 2857.57
     495 2866.82     565 2900.46   571.2 2901.32     586 2900.38   590.8  2901.4
#Mann= 9 ,-1 , 0
       0     .12       0  113.44    .016       0  164.15     .12       0
  217.66     .08       0  255.13     .06       0  271.17     .12       0
     343     .04       0   365.4     .12       0  586.13     .06       0
Bank Sta=343,365.4
XS Rating Curve= 0 ,0
Exp/Cntr=0.3,0.1

Type RM Length L Ch R = 1 ,36851   ,192.3,192.3,192.3
XS GIS Cut Line= 4
     2048919.544      383173.432     2048556.122      383180.026
     2048471.128      383177.828     2048300.407      383158.045
#Sta/Elev= 30
       0 2876.68    46.1 2857.76    52.7  2853.5    62.5 2845.22    65.8 2843.99
    72.3 2844.58     102 2846.48     134 2846.16   160.9 2841.03   170.8 2842.63
   193.8 2840.93   203.6 2839.27   213.4 2835.42     220 2834.51     279 2833.88
   338.1 2833.38   380.8 2834.07   389.7 2830.95   397.9 2830.03   409.32830.767
   416.9 2833.35   426.7 2839.48   433.3 2840.92   449.1 2846.96   462.9 2856.14
   478.7 2864.22   492.7 2868.43   522.4 2881.05   591.7  2903.2   620.4 2908.18
#Mann= 9 ,-1 , 0
       0     .12       0    72.3    .016       0     102     .12       0
   160.9     .08       0     220     .12       0     279     .06       0
   338.1     .12       0   389.7     .04       0   409.3     .12       0
Bank Sta=389.7,409.3
XS Rating Curve= 0 ,0
Exp/Cntr=0.5,0.3

Type RM Length L Ch R = 1 ,36658   ,73,73,73
XS GIS Cut Line= 4
     2048915.153      383138.914     2048641.669      383091.587
     2048573.422      382941.444     2048341.384      382831.009
#Sta/Elev= 30
       0 2879.36    55.6 2862.12      70 2853.33    92.3 2842.11   131.9 2844.32
   148.9 2844.19   165.5 2841.17   175.5 2836.63   188.8 2835.67   198.8 2839.42
   212.1 2841.31   235.4 2839.57   248.6 2835.34   262.1 2831.95   279.5 2831.92
   311.8 2831.56   348.72829.118   358.8 2827.21   367.42828.821   391.2 2831.49
   453.1 2830.95   484.4 2840.56   502.6 2837.03   517.2  2837.8   532.3 2843.97
   564.4    2853   593.4 2865.91   632.8 2877.74   662.8 2889.74   699.5 2899.89
#Mann= 9 ,-1 , 0
       0     .12       0      70    .016       0   131.9     .12       0
   188.8     .08       0   248.6     .12       0   279.5     .06       0
   311.8     .12       0   348.7     .04       0   367.4     .12       0
#XS Ineff= 2 , 0
          340.31 2837.86  376.74         2837.86
Permanent Ineff=
       F       F
Bank Sta=348.7,367.4
XS Rating Curve= 0 ,0
Exp/Cntr=0.5,0.3

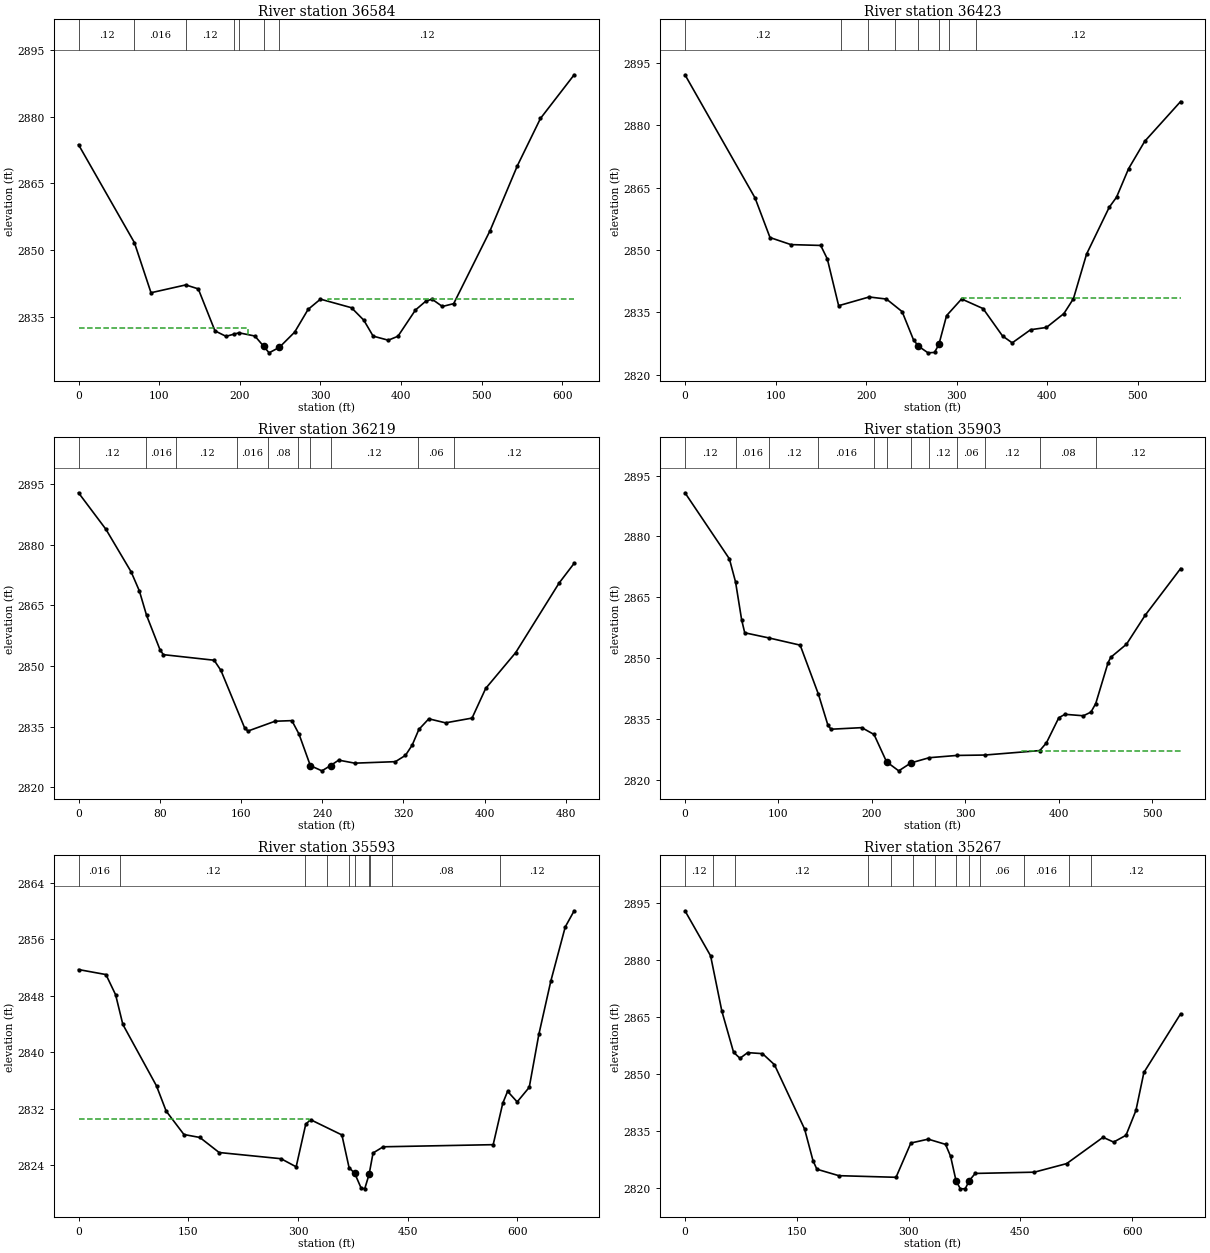
Type RM Length L Ch R = 1 ,36584   ,163.3,163.3,163.3
XS GIS Cut Line= 4
     2048883.641      383094.299     2048698.267       383034.95
     2048664.562      382969.739     2048368.549      382789.493
#Sta/Elev= 30
       0 2873.73    69.3 2851.71    89.9 2840.44     133  2842.2   148.5 2841.31
   169.2 2831.87   182.9 2830.64   193.3 2831.16     199 2831.43   218.7 2830.71
   229.82828.362   236.3 2826.93   249.12828.174     268 2831.58   284.7  2836.7
     300    2839   338.5 2837.07   353.8 2834.26   365.3 2830.69   384.1 2829.77
   396.1 2830.66   417.8 2836.56   430.6 2838.54   438.3    2839   451.2 2837.35
   465.2 2837.99   510.3 2854.39   544.3 2869.04   572.8 2879.62   614.6 2889.44
#Mann= 7 ,-1 , 0
       0     .12       0    69.3    .016       0     133     .12       0
   193.3     .08       0     199     .12       0   229.8     .04       0
   249.1     .12       0
#XS Ineff= 2 , 0
          209.69  2832.6  309.04         2839.08
Permanent Ineff=
       F       F
Bank Sta=229.8,249.1
XS Rating Curve= 0 ,0
Exp/Cntr=0.5,0.3

Type RM Length L Ch R = 1 ,36423   ,212,212,212
XS GIS Cut Line= 4
     2048901.226      382870.091     2048677.018      382847.377
     2048581.034      382862.764      2048374.41      382774.107
#Sta/Elev= 30
       0 2892.16    77.4 2862.52    93.9    2853     117  2851.3   149.9  2851.1
   157.2 2847.85   169.7  2836.6   203.4  2838.7   222.5  2838.2   239.8 2835.18
   252.4 2828.38   257.82826.874   268.4 2825.26   275.6 2825.36   280.4 2827.27
   288.9 2834.21   305.5 2838.22   329.2 2835.91   350.7 2829.32   361.4 2827.66
   381.7 2830.82   399.2 2831.37   418.5 2834.71     429 2838.28   443.5 2849.01
   468.5 2860.27   476.6  2862.7   489.9 2869.56   507.7 2876.14   547.4 2885.73
#Mann= 8 ,-1 , 0
       0     .12       0  172.41    .016       0  202.09     .08       0
  231.84     .12       0   257.8     .04       0   280.4     .12       0
  291.66     .08       0  321.57     .12       0
#XS Ineff= 2 , 0
                          306.27         2838.49
Permanent Ineff=
       F       F
Bank Sta=257.8,280.4
XS Rating Curve= 0 ,0
Exp/Cntr=0.3,0.1

Type RM Length L Ch R = 1 ,36219   ,315.7,315.7,315.7
XS GIS Cut Line= 3
     2048883.641      382697.172     2048680.682       382661.27
     2048399.322      382639.289
#Sta/Elev= 30
       0 2892.85      27 2883.82    51.8 2873.31    59.9 2868.61      67 2862.57
    80.3 2854.01    83.6 2852.81   133.6 2851.43   140.3 2848.91   163.6 2834.72
   166.9 2833.91   193.6 2836.34   210.2 2836.49   217.2 2833.17   228.42825.352
   239.8 2824.07   248.3 2825.37   256.3 2826.72   272.1 2825.97   312.2 2826.34
   322.1  2827.9   328.7 2830.42   335.3 2834.31   345.1 2836.94   361.6 2835.94
   387.7 2837.12   401.1 2844.44   430.7 2853.32   473.5 2870.54   488.3 2875.41
#Mann= 10 ,-1 , 0
       0     .12       0   66.34    .016       0   96.34     .12       0
  156.33    .016       0  186.33     .08       0   216.2     .12       0
   228.4     .04       0   248.3     .12       0   334.7     .06       0
  369.66     .12       0
Bank Sta=228.4,248.3
XS Rating Curve= 0 ,0
Exp/Cntr=0.3,0.1

Type RM Length L Ch R = 1 ,35903   ,308.2,308.2,308.2
XS GIS Cut Line= 2
     2048901.078      382363.467     2048372.851      382318.797
#Sta/Elev= 30
       0 2890.76    47.5 2874.45    54.1 2868.74    60.6 2859.41    63.9 2856.21
    90.3 2854.91   123.2 2853.16   142.8 2840.99   152.8 2833.46   156.1 2832.41
   189.1  2832.8   202.2 2831.11   215.6 2824.37   228.6 2822.14   241.7  2824.1
   261.2 2825.38   290.7 2825.94   320.8 2826.04   379.5 2827.14   386.6 2829.06
   399.8 2835.24   406.4 2836.09   426.1 2835.73   434.2 2836.64   439.3 2838.74
   452.5 2848.84   455.4 2850.16   472.2 2853.39   492.1 2860.51   530.1 2872.07
#Mann= 12 ,-1 , 0
       0     .12       0    54.1    .016       0    90.3     .12       0
   142.8    .016       0   202.2     .12       0   215.6     .04       0
   241.7    .016       0   261.2     .12       0   290.7     .06       0
   320.8     .12       0   379.5     .08       0   439.3     .12       0
#XS Ineff= 2 , 0
                          360.88         2827.04
Permanent Ineff=
       F       F
Bank Sta=215.6,241.7
XS Rating Curve= 0 ,0
Exp/Cntr=0.3,0.1

Type RM Length L Ch R = 1 ,35593   ,322.9,322.9,322.9
XS GIS Cut Line= 3
     2049068.344       382062.19     2048730.834      382036.132
     2048392.084      382049.781
#Sta/Elev= 30
       0  2851.7    37.5 2850.99    50.7 2848.13    60.6 2843.92   106.6 2835.21
   119.8 2831.64   144.1 2828.32   165.9  2827.9   192.2 2825.77   276.8 2824.89
   297.5 2823.74   310.6 2829.78   317.2 2830.42     360 2828.26   369.8 2823.64
   377.62822.797   386.2 2820.75   391.2 2820.62   397.22822.673   402.6  2825.7
   416.5 2826.58   566.8 2826.88   579.9 2832.75   586.5 2834.44   599.6 2832.94
   616.1 2835.01   629.2  2842.5   645.6 2850.07   665.3 2857.74   677.5 2860.03
#Mann= 10 ,-1 , 0
       0    .016       0   57.08     .12       0  310.02    .016       0
  339.64     .08       0   369.2     .12       0   377.6     .04       0
   397.2     .12       0  398.76    .016       0  428.33     .08       0
  576.13     .12       0
#XS Ineff= 2 , 0
          314.58 2830.49
Permanent Ineff=
       F       F
Bank Sta=377.6,397.2
XS Rating Curve= 0 ,0
Exp/Cntr=0.3,0.1

Type RM Length L Ch R = 1 ,35267   ,61.8,61.8,61.8
XS GIS Cut Line= 2
     2049002.579      381665.119     2048344.932      381764.387
#Sta/Elev= 30
       0 2892.95    34.4 2881.07    49.5 2866.49    65.2 2855.68    73.8 2854.08
    84.1 2855.58     104 2855.31     120 2852.41   160.5 2835.45   171.8 2827.11
     177 2824.86   206.4 2823.16   283.2 2822.73   303.1 2831.76   326.4 2832.78
   349.6 2831.41   356.4 2828.27   363.72821.836   369.5 2819.69   376.1 2819.72
   381.32821.798   389.4 2823.75   468.8 2824.08   512.2 2826.34     561 2833.27
   575.2 2832.01   591.8  2833.8   605.1 2840.33   615.8 2850.35   665.1 2865.81
#Mann= 13 ,-1 , 0
       0     .12       0   36.99      .1       0   66.86     .12       0
  246.09    .016       0  275.96     .12       0  305.83    .016       0
   335.7     .12       0   363.7     .04       0   381.3     .12       0
  395.45     .06       0  455.19    .016       0  514.93     .06       0
  544.81     .12       0
#XS Ineff= 2 , 0
          306.27 2831.82
Permanent Ineff=
       F       F
Bank Sta=363.7,381.3
XS Rating Curve= 0 ,0
Exp/Cntr=0.3,0.1