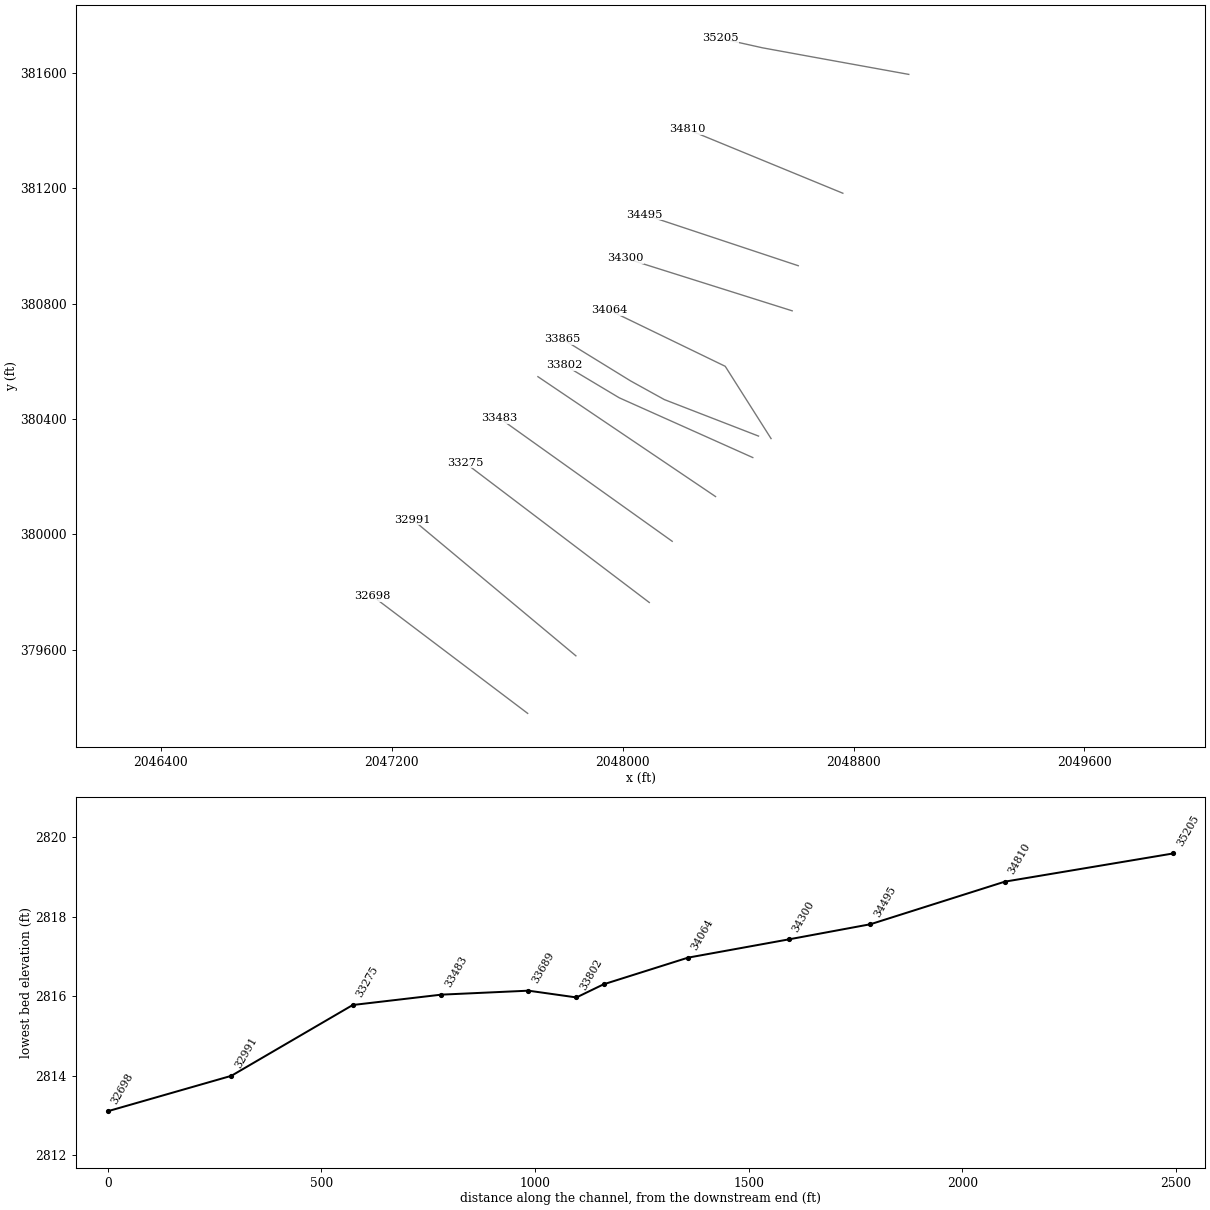
HEC-RAS study MEADOWCK2.prj: MEADOWCK2

--- MEADOWCK2.g01 (geometry) --- (continued)

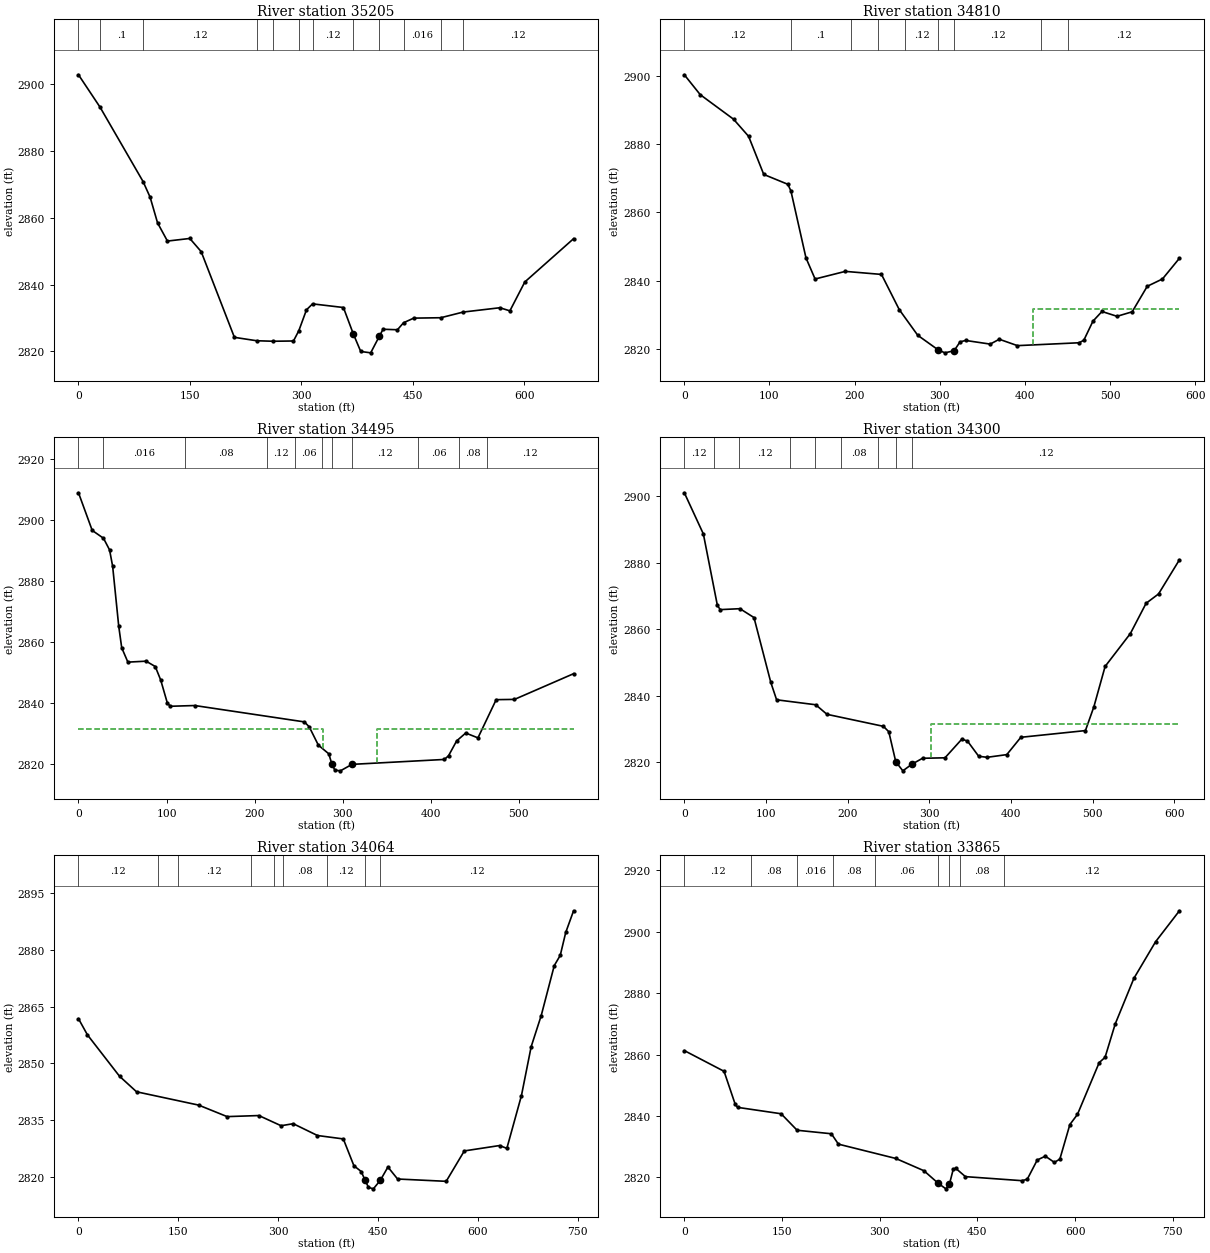
Type RM Length L Ch R = 1 ,35205   ,394.6,394.6,394.6
XS GIS Cut Line= 4
2048991.27425596381595.1652457462048659.45538866381655.325040384
 2048484.6159855381687.2849312862048337.03648927381720.184818978
#Sta/Elev= 30
       0 2902.83      29 2893.14    86.9 2870.87    96.4 2866.18   106.4 2858.49
   119.7 2853.05   149.8 2853.83   165.1 2849.89   209.8 2824.23   239.8 2823.21
     262 2823.06   289.3 2823.14   296.5 2826.22   306.8 2832.47     315 2834.25
   356.5 2833.16   369.8 2825.26   379.8    2820   393.2 2819.59   404.7  2824.5
   409.8 2826.65   429.2  2826.5   437.4  2828.6   451.1 2829.98   487.5  2830.1
   517.7  2831.8     567 2833.09   580.5 2832.16   600.6 2840.81   666.2 2853.76
#Mann= 12 ,-1 , 0
       0     .12       0      29      .1       0    86.9     .12       0
   239.8    .016       0     262     .12       0   296.5    .016       0
     315     .12       0   369.8     .04       0   404.7     .06       0
   437.4    .016       0   487.5     .06       0   517.7     .12       0
Bank Sta=369.8,404.7
XS Rating Curve= 0 ,0
Exp/Cntr(USF)=0,0
Exp/Cntr=0.3,0.1

Type RM Length L Ch R = 1 ,34810   ,314.5,314.5,314.5
XS GIS Cut Line= 2
     2048762.856      381183.105     2048224.987       381404.38
#Sta/Elev= 30
       0 2900.33    18.7  2894.5    57.8 2887.32    75.5  2882.3    93.3 2871.14
   121.6 2868.25   125.2 2866.31   142.9 2846.69   153.6 2840.51   189.1 2842.74
   231.6 2841.85   252.5 2831.53   274.2 2824.02   298.32819.728   306.1 2818.88
   316.92819.495   323.9 2822.09   330.4 2822.51   359.3 2821.44     370 2822.86
   391.3 2820.99   463.7 2821.83   469.3 2822.57     480 2828.15   490.6 2830.99
   508.3 2829.58   526.1  2830.9   543.8 2838.37   561.7 2840.52   581.6 2846.58
#Mann= 9 ,-1 , 0
       0     .12       0  125.25      .1       0  195.53    .016       0
  227.47     .08       0  259.41     .12       0   298.3     .04       0
   316.9     .12       0   419.1    .016       0  451.04     .12       0
#XS Ineff= 2 , 0
                          409.97         2831.58
Permanent Ineff=
       F       F
Bank Sta=298.3,316.9
XS Rating Curve= 0 ,0
Exp/Cntr=0.3,0.1

Type RM Length L Ch R = 1 ,34495   ,190.8,190.8,190.8
XS GIS Cut Line= 2
     2048608.406      380931.751     2048074.843      381109.192
#Sta/Elev= 30
       0 2908.84    15.6 2896.52    28.4 2893.95    35.3 2890.14    38.8 2884.78
    45.7 2865.17    49.1  2858.1    56.1  2853.4    76.8 2853.71    87.2 2851.96
    93.4 2847.53     101 2839.92   104.5 2838.95   132.1 2839.19   256.6 2833.83
   262.1  2832.2   272.4 2826.24   284.3 2823.38   287.7 2820.12   291.2 2818.02
   297.5 2817.81   310.62819.929   415.6 2821.54   420.3 2822.76   429.5 2827.61
   439.8 2830.19   453.7  2828.6   474.4 2841.11   495.2  2841.2   562.3 2849.61
#Mann= 11 ,-1 , 0
       0     .12       0   27.79    .016       0  121.18     .08       0
  214.56     .12       0  245.69     .06       0  276.82     .12       0
   287.7     .04       0   310.6     .12       0  385.91     .06       0
  432.45     .08       0  463.58     .12       0
#XS Ineff= 2 , 0
          277.74 2831.36  339.53         2831.36
Permanent Ineff=
       F       F
Bank Sta=287.7,310.6
XS Rating Curve= 0 ,0
Exp/Cntr=0.3,0.1

Type RM Length L Ch R = 1 ,34300   ,236.1,236.1,236.1
XS GIS Cut Line= 2
     2048587.312      380775.405     2048009.078      380957.809
#Sta/Elev= 30
       0 2901.08    23.3  2888.7    40.5 2867.17      44 2865.93    68.1 2866.21
    85.3 2863.54   105.9 2844.03     113  2838.8   160.9 2837.31   174.7 2834.43
   243.8 2830.82   250.4 2829.19   258.92820.198   267.6 2817.43   278.62819.411
   291.7 2821.21   319.2 2821.35   339.8 2826.95   346.7  2826.4   360.5 2821.81
   370.8  2821.5   394.9 2822.31   412.1 2827.52   491.2 2829.54   501.5 2836.67
   515.3 2848.84   546.2 2858.72   565.5 2867.84   580.7 2870.64   606.3 2880.91
#Mann= 9 ,-1 , 0
       0     .12       0   36.51    .016       0   67.48     .12       0
  129.42    .016       0  160.39     .12       0  191.37     .08       0
  237.23     .12       0   258.9     .04       0   278.6     .12       0
#XS Ineff= 2 , 0
                          301.55         2831.58
Permanent Ineff=
       F       F
Bank Sta=258.9,278.6
XS Rating Curve= 0 ,0
Exp/Cntr=0.3,0.1

Type RM Length L Ch R = 1 ,34064   ,197.6,197.6,197.6
XS GIS Cut Line= 3
     2048514.102      380332.423     2048355.274      380583.074
      2047953.24      380777.886
#Sta/Elev= 30
       0 2861.79    13.4 2857.55    61.6 2846.64    87.2 2842.54   180.5 2839.03
   223.2    2836   270.9 2836.28   304.2  2833.6   322.5 2834.13   358.9 2831.02
   397.7 2830.12   413.6 2823.06   424.6 2821.53   430.42819.228   435.5 2817.36
   442.8 2816.97   453.32819.218   464.7 2822.72   479.2 2819.56   552.2 2818.95
   579.4 2826.96   632.4 2828.38   643.3 2827.63   665.2 2841.53   679.8 2854.41
   694.9 2862.62   714.5 2875.79   723.5 2878.49   731.7 2884.51   743.5 2890.23
#Mann= 9 ,-1 , 0
       0     .12       0  119.37     .08       0     149     .12       0
  259.24    .016       0  294.21     .12       0  307.33     .08       0
  372.98     .12       0   430.4     .04       0   453.3     .12       0
Bank Sta=430.4,453.3
XS Rating Curve= 0 ,0
Exp/Cntr=0.3,0.1

Type RM Length L Ch R = 1 ,33865   ,63.5,63.5,63.5
XS GIS Cut Line= 4
     2048470.672      380341.109      2048144.33      380467.675
     2048027.691      380532.199      2047791.93      380677.378
#Sta/Elev= 30
       0 2861.28      61 2854.54    78.2 2843.76    81.8 2842.81   148.6 2840.73
   173.2 2835.36   225.8 2834.22   236.6 2830.84   324.6 2826.19   367.9 2822.19
   389.92818.094   401.6  2816.3   407.12817.876   412.9 2822.65   416.6    2823
   431.6 2820.27   518.2 2818.96   526.5  2819.4   541.9 2825.68   554.3 2826.93
   568.2  2824.9   576.6 2825.98     592 2837.22   603.6  2840.5     637 2857.37
     646 2859.08   661.6 2869.94   690.3 2884.79   723.6  2896.7   760.2 2906.77
#Mann= 9 ,-1 , 0
       0     .12       0  102.32     .08       0  173.15    .016       0
  229.04     .08       0   292.4     .06       0  389.89     .04       0
   407.1     .12       0  423.65     .08       0  491.38     .12       0
Bank Sta=389.9,407.1
XS Rating Curve= 0 ,0
Exp/Cntr=0.3,0.1

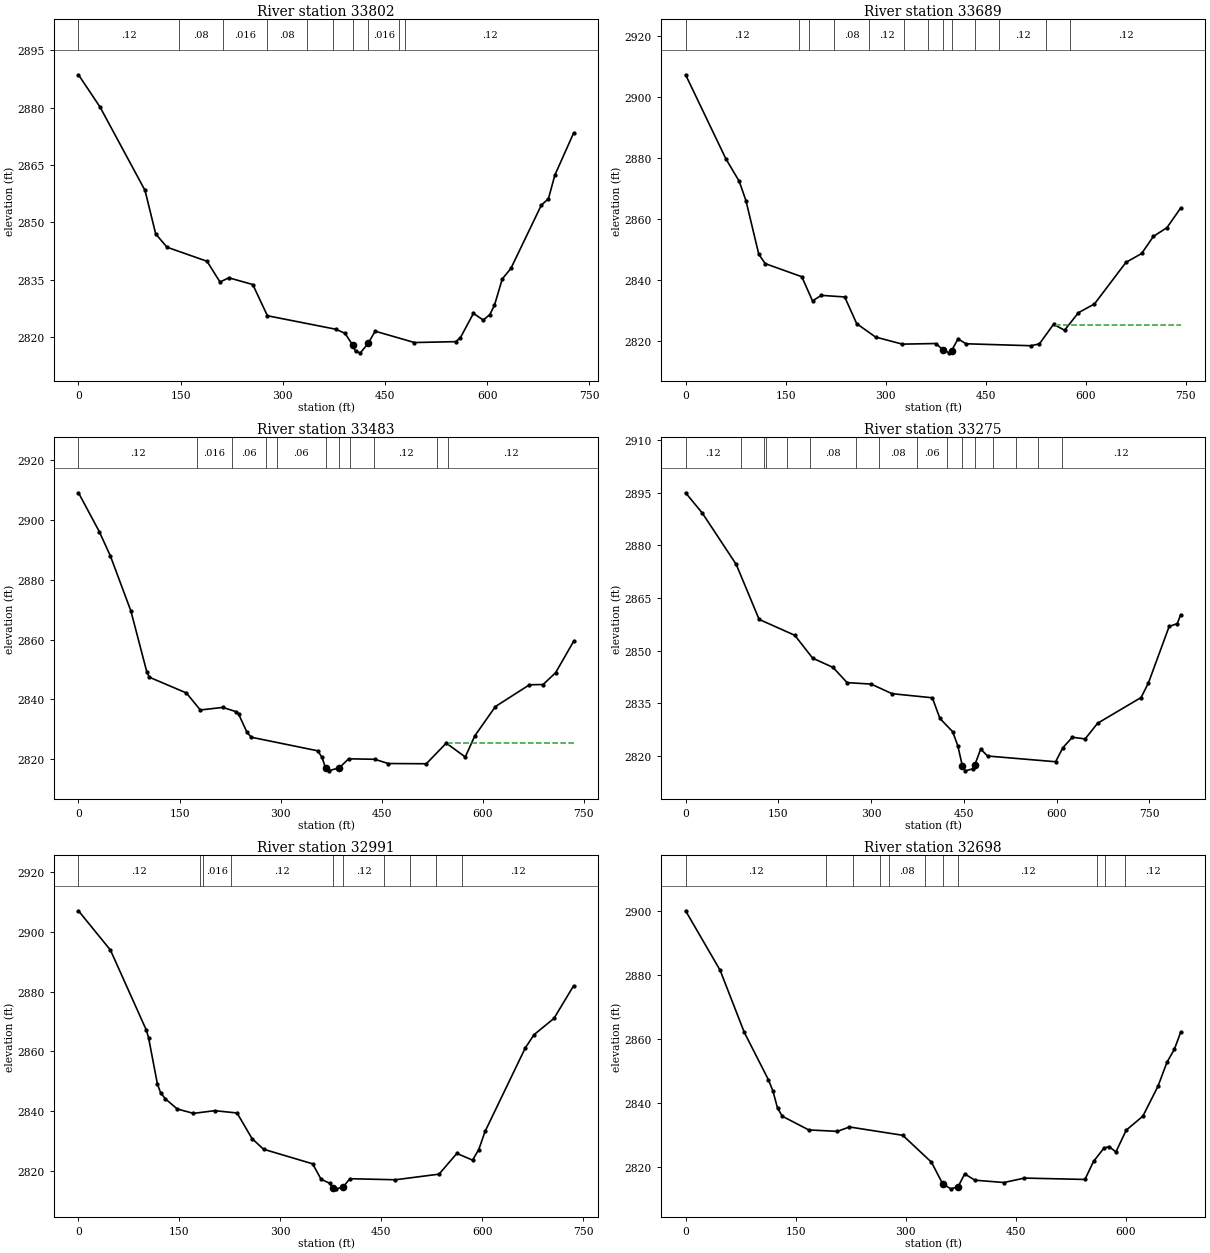
Type RM Length L Ch R = 1 ,33802   ,112.3,112.3,112.3
XS GIS Cut Line= 3
     2048450.819      380266.658     2047987.984       380473.88
     2047799.375      380586.796
#Sta/Elev= 30
       0 2888.54    31.5 2880.17    97.7 2858.36   113.4 2846.99   130.1 2843.53
   188.7 2839.87   207.8 2834.46   220.8 2835.55   255.9  2833.8   277.4 2825.65
   378.1 2822.12   391.5 2821.05   402.42818.025   406.8 2816.33   413.9 2815.97
   425.32818.437   435.6 2821.62   493.3 2818.66     554 2818.89   560.8 2819.93
   579.9 2826.27   594.3 2824.53   603.9 2825.94   610.8 2828.38   622.2 2835.24
     635 2838.03   679.6 2854.52     690 2856.17   699.5 2862.37   726.9 2873.29
#Mann= 10 ,-1 , 0
       0     .12       0  147.49     .08       0  212.22    .016       0
  276.94     .08       0  335.41    .016       0  374.03     .12       0
   402.4     .04       0   425.3    .016       0  471.12     .08       0
  479.97     .12       0
Bank Sta=402.4,425.3
XS Rating Curve= 0 ,0
Exp/Cntr=0.3,0.1

Type RM Length L Ch R = 1 ,33689   ,204.2,204.2,204.2
XS GIS Cut Line= 2
     2048321.771      380131.406     2047706.312      380547.089
#Sta/Elev= 30
       0 2907.22    60.4  2879.7    80.5  2872.3    90.5 2866.02   109.8 2848.42
   119.5 2845.36   174.3 2841.07   190.4 2833.15   203.6 2834.97   238.7 2834.44
   256.7 2825.69   284.9 2821.32   325.1 2818.99   375.5 2819.19   386.12817.133
   395.3 2816.14   399.22816.896   408.7 2820.74   420.5 2819.11     518 2818.47
   530.7 2819.06     552 2825.49   568.5 2823.54   589.3 2829.28   613.4 2832.16
   660.6 2845.77   684.2 2848.68   701.8 2854.28   722.1 2857.14   742.7 2863.58
#Mann= 13 ,-1 , 0
       0     .12       0  169.89     .08       0  184.93    .016       0
  222.66     .08       0  275.44     .12       0  328.21     .06       0
  363.15     .12       0   386.1     .04       0   399.2    .016       0
  434.43     .06       0  470.08     .12       0  541.36     .08       0
  577.01     .12       0
#XS Ineff= 2 , 0
                          555.79         2825.18
Permanent Ineff=
       F       F
Bank Sta=386.1,399.2
XS Rating Curve= 0 ,0
Exp/Cntr=0.3,0.1

Type RM Length L Ch R = 1 ,33483   ,207,207,207
XS GIS Cut Line= 2
     2048171.629      379976.301     2047573.541      380403.151
#Sta/Elev= 30
       0 2909.15    30.8 2896.18    47.3 2888.02    77.8 2869.56   101.3 2849.27
   105.1  2847.4   160.2 2842.11   180.8 2836.42   214.2 2837.28   234.1 2835.84
   237.8 2834.98   250.2 2828.89   256.6 2827.29     355 2822.75   361.5 2820.53
   366.72816.983   371.2 2816.04   387.12817.069     401 2820.07   439.7 2819.91
   459.8 2818.49   516.3 2818.41   545.9 2825.33   574.1 2820.67   588.2 2827.74
   618.8 2837.56   669.4 2844.86   689.6 2844.94   708.2  2848.9   734.8 2859.36
#Mann= 11 ,-1 , 0
       0     .12       0  176.46    .016       0   227.3     .06       0
  278.15     .12       0  294.12     .06       0   366.7     .04       0
   387.1     .12       0  402.99    .016       0  439.27     .12       0
  532.37     .08       0  548.14     .12       0
#XS Ineff= 2 , 0
                          549.92         2825.48
Permanent Ineff=
       F       F
Bank Sta=366.7,387.1
XS Rating Curve= 0 ,0
Exp/Cntr=0.3,0.1

Type RM Length L Ch R = 1 ,33275   ,284.1,284.1,284.1
XS GIS Cut Line= 2
     2048092.215      379764.116      2047454.42      380248.046
#Sta/Elev= 30
       0 2894.99    27.1 2889.19    81.9 2874.57   118.9 2858.92   176.6 2854.39
   205.4 2847.89   238.4 2845.24   261.2 2840.91   300.1 2840.49   333.8 2837.76
     399 2836.59   411.3  2830.7   431.9 2826.92   440.2 2822.92   447.72817.081
   452.5 2815.78   464.9 2816.37   467.82817.511   477.2 2821.98   488.4    2820
   598.4 2818.37   610.1 2822.37   625.5 2825.35   646.1 2824.87   666.3 2829.34
   736.6 2836.67   748.3 2840.74     782 2856.92   795.1 2857.71   800.6 2860.26
#Mann= 16 ,-1 , 0
       0     .12       0    89.6    .016       0  126.67     .12       0
   129.7    .016       0  163.75     .12       0  200.83     .08       0
  274.98    .016       0  312.06     .08       0  374.02     .06       0
  423.29     .12       0   447.7     .04       0   467.8     .12       0
  497.45    .016       0  534.52     .08       0  569.48     .06       0
  608.68     .12       0
Bank Sta=447.7,467.8
XS Rating Curve= 0 ,0
Exp/Cntr=0.3,0.1

Type RM Length L Ch R = 1 ,32991   ,289.2,289.2,289.2
XS GIS Cut Line= 2
     2047837.841       379579.23     2047273.257      380050.751
#Sta/Elev= 30
       0  2907.1    47.5 2893.93     101 2867.05   104.1 2864.63   117.3 2849.07
     122  2846.2     129 2844.15   146.8 2840.73   170.9 2839.27   202.4 2840.17
   235.6  2839.4   257.9 2830.82     275 2827.26   347.9 2822.38   360.5 2817.19
   373.4 2815.85   377.82814.233   381.9    2814   392.82814.504   403.3 2817.39
     471 2817.04   535.8 2818.92   562.2 2825.87   585.5 2823.61   594.8 2827.16
   604.1  2833.2     664 2861.22   676.9 2865.62   706.5 2871.06   735.6 2881.95
#Mann= 10 ,-1 , 0
       0     .12       0  180.33     .08       0  184.89    .016       0
  226.41     .12       0   377.8     .04       0   392.8     .12       0
  454.27     .08       0  492.76    .016       0  531.24     .08       0
  569.72     .12       0
Bank Sta=377.8,392.8
XS Rating Curve= 0 ,0
Exp/Cntr=0.3,0.1

Type RM Length L Ch R = 1 ,32698   ,333.9,333.9,333.9
XS GIS Cut Line= 2
     2047670.783      379379.681     2047132.914      379786.487
#Sta/Elev= 30
       0  2900.2      47 2881.58    79.9 2862.14   112.8 2847.28   118.9 2843.78
   125.2 2838.43   131.8 2835.84   167.8 2831.56   206.8 2831.11   223.2 2832.49
   295.8 2829.88   334.9 2821.46   350.32814.655   361.3 2813.11   371.12813.747
   380.2 2817.78   394.1 2815.82   433.7 2815.09   461.5 2816.48     544 2816.05
   555.7 2821.69   569.8 2825.84   576.8 2826.36   586.2 2824.66   600.2 2831.48
   622.9 2835.87   643.5 2845.24   655.8 2852.78   665.8 2856.81   674.4 2862.14
#Mann= 11 ,-1 , 0
       0     .12       0  190.67     .08       0   227.7    .016       0
  264.74     .12       0   277.6     .08       0  326.57     .12       0
   350.3     .04       0   371.1     .12       0  561.01     .08       0
  571.39     .06       0  598.04     .12       0
Bank Sta=350.3,371.1
XS Rating Curve= 0 ,0
Exp/Cntr=0.3,0.1