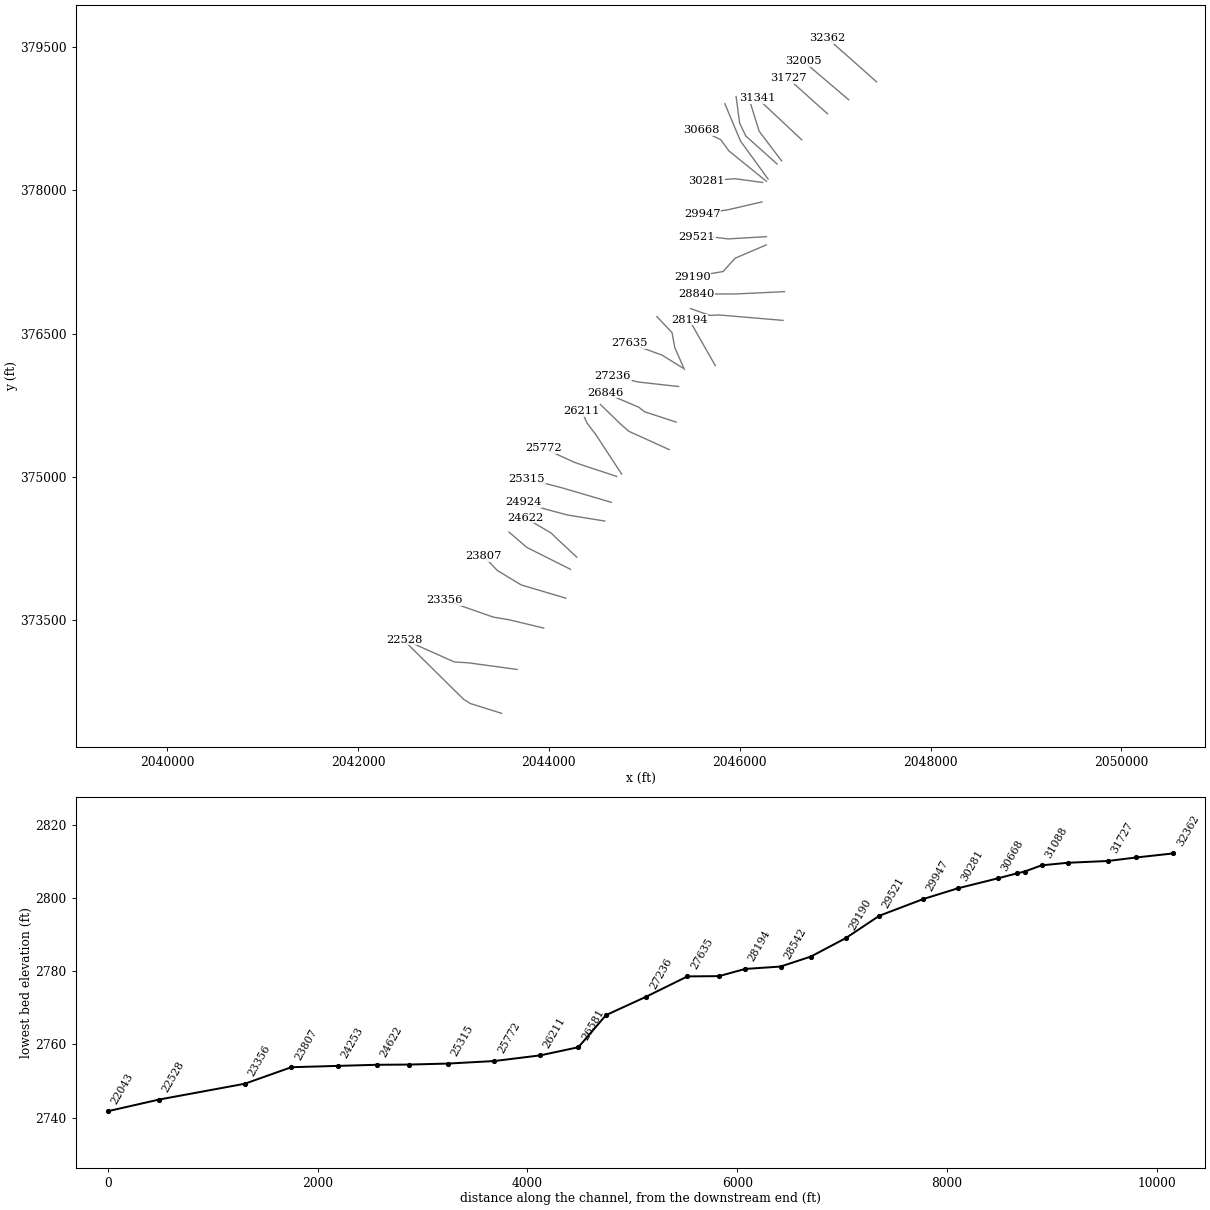
HEC-RAS study MEADOWCK2.prj: MEADOWCK2

--- MEADOWCK2.g01 (geometry) --- (continued)

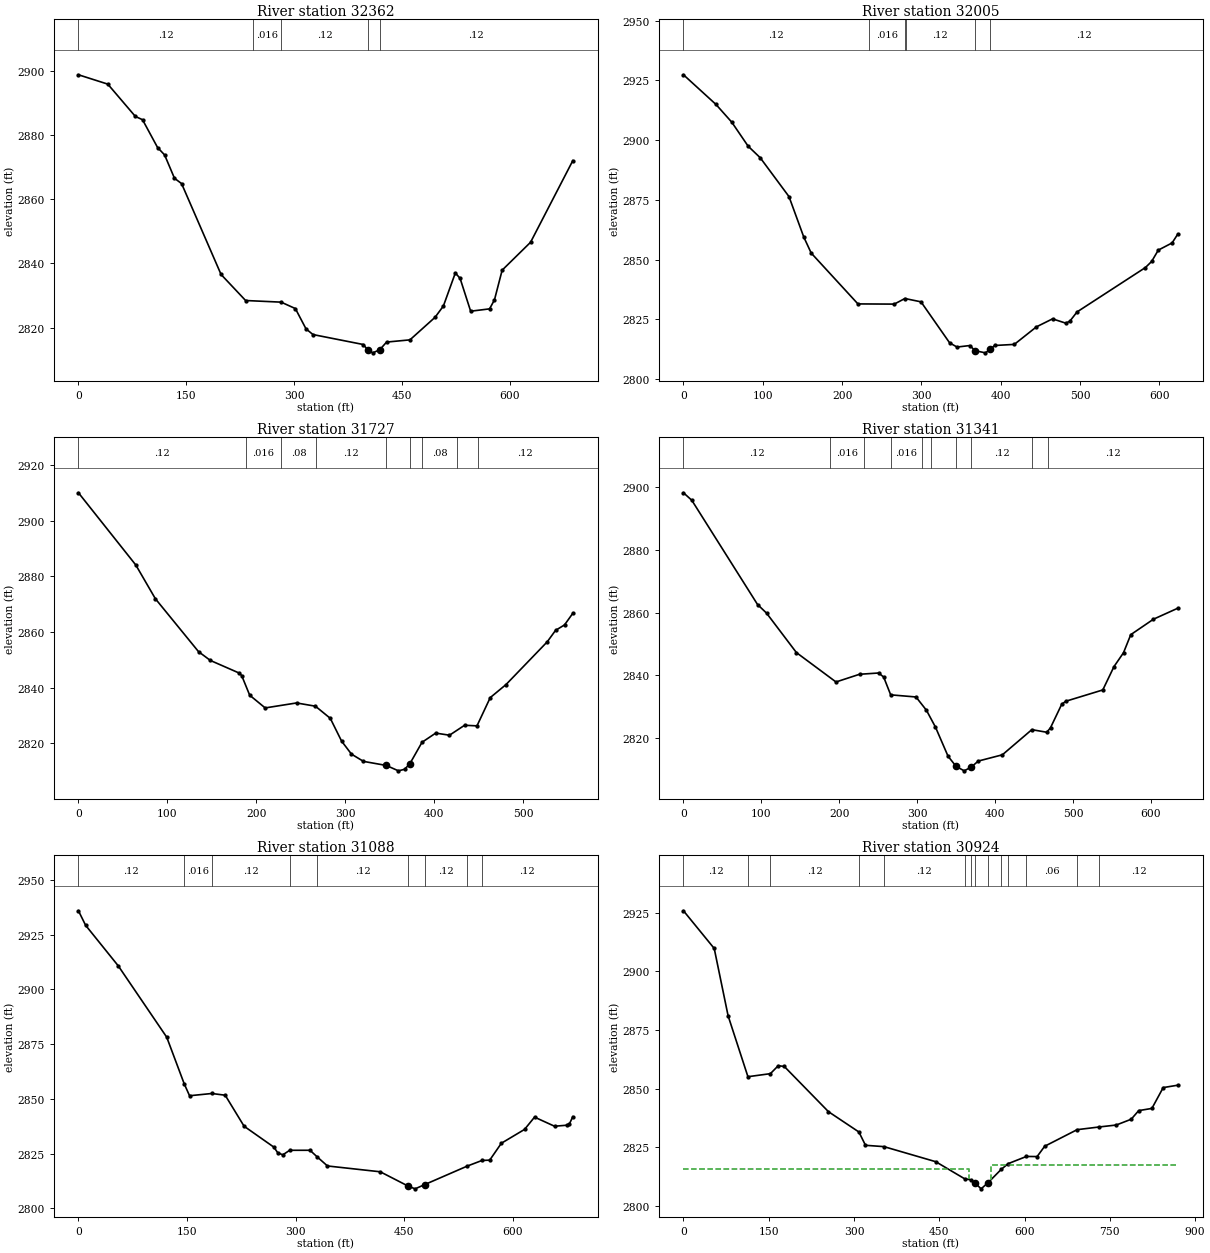
Type RM Length L Ch R = 1 ,32362   ,354.1,354.1,354.1
XS GIS Cut Line= 2
     2047434.189      379139.682     2046920.149       379595.85
#Sta/Elev= 30
       0 2898.72    40.8 2895.81    79.1 2885.76    89.1 2884.73     110 2876.08
   119.8 2873.77   133.5 2866.51   143.4 2864.84   198.3 2836.55   232.4 2828.45
   281.8 2827.94   301.6 2825.94   316.4 2819.62   326.1 2817.85   396.1 2814.75
   402.52812.966   409.3 2812.16   418.92813.122   428.4 2815.51   460.9  2816.2
   495.8 2823.22   507.4 2826.74     524 2837.03   530.6 2835.35   545.3 2825.12
   571.6 2825.85   578.4 2828.65   589.1  2837.9   628.6 2846.58   687.3 2871.98
#Mann= 5 ,-1 , 0
       0     .12       0   242.4    .016       0  281.89     .12       0
   402.5     .04       0   418.9     .12       0
Bank Sta=402.5,418.9
XS Rating Curve= 0 ,0
Exp/Cntr=0.3,0.1

Type RM Length L Ch R = 1 ,32005   ,270.9,270.9,270.9
XS GIS Cut Line= 2
     2047141.424      378952.449     2046666.533      379355.851
#Sta/Elev= 30
       0 2927.34    40.9 2914.96    60.9 2907.51    81.5 2897.48    96.7 2892.66
     133  2876.4   151.6 2859.51     161 2852.78   219.9 2831.51   265.7 2831.43
   279.1 2833.77   299.4 2832.38   335.5 2815.22   344.8 2813.47   361.1 2814.11
   367.32811.967   380.5 2811.05     3872812.507   392.1 2814.12     417 2814.58
   444.9 2821.92   465.2 2825.26   481.8 2823.47   486.9 2824.24   496.1 2828.16
   582.3 2846.73   590.1 2849.26   598.5 2854.01   615.9 2857.02   623.1 2860.72
#Mann= 6 ,-1 , 0
       0     .12       0  234.21    .016       0  279.83     .06       0
  280.06     .12       0   367.3     .04       0     387     .12       0
Bank Sta=367.3,387
XS Rating Curve= 0 ,0
Exp/Cntr=0.3,0.1

Type RM Length L Ch R = 1 ,31727   ,383,383,383
XS GIS Cut Line= 2
     2046920.149      378804.364     2046506.534      379175.426
#Sta/Elev= 30
       0 2910.07    64.5 2884.09    86.5 2871.96     135 2852.94   148.3 2849.78
   180.9 2845.22   183.5 2844.34   192.5 2837.29   209.9 2832.71   245.2  2834.5
   266.4 2833.33   283.1 2828.97   295.8 2820.78   306.9  2816.1   320.4 2813.49
   346.12812.024   359.7 2810.09   366.7 2810.66   372.6 2812.67   386.2 2820.35
   401.6 2823.66   417.1  2822.9   434.1 2826.48     448 2826.26   462.9 2836.42
   480.6  2841.1     527 2856.49   536.3 2860.59   546.4 2862.56   555.7 2866.72
#Mann= 9 ,-1 , 0
       0     .12       0  187.89    .016       0  227.66     .08       0
  267.25     .12       0   346.1     .04       0   372.6     .12       0
   386.3     .08       0  425.98     .06       0  448.82     .12       0
Bank Sta=346.1,372.6
XS Rating Curve= 0 ,0
Exp/Cntr=0.3,0.1

Type RM Length L Ch R = 1 ,31341   ,249,249,249
XS GIS Cut Line= 2
     2046649.512      378532.025     2046186.536      378966.066
#Sta/Elev= 30
       0 2898.18    10.7 2895.79    95.1 2862.58   106.6 2859.86     145 2847.27
   195.8 2837.91     226 2840.36   250.5 2840.77     257 2839.48     266 2833.81
   298.5 2833.13   311.9  2828.9   323.5 2823.53   339.7 2814.23     3502811.025
   360.4  2809.6   369.62810.836   378.4 2812.71   409.4 2814.71   447.2 2822.72
   466.4 2821.89   471.2 2823.34   485.6 2830.82   490.8 2831.77   538.3 2835.37
   552.7 2842.82   564.9 2847.23   574.2 2852.98   603.3  2857.9   634.6 2861.41
#Mann= 10 ,-1 , 0
       0     .12       0   188.6    .016       0  231.79     .12       0
  266.09    .016       0  306.58     .06       0  318.16     .12       0
     350     .04       0   369.6     .12       0  447.72    .016       0
  468.53     .12       0
Bank Sta=350,369.6
XS Rating Curve= 0 ,0
Exp/Cntr=0.3,0.1

Type RM Length L Ch R = 1 ,31088   ,161.8,161.8,161.8
XS GIS Cut Line= 3
     2046438.449       378310.75     2046203.557      378622.238
     2046116.749      378901.385
#Sta/Elev= 30
       0 2935.93     9.9  2929.3      55 2910.75   121.9 2878.17   146.1 2856.81
   153.4 2851.43   184.2 2852.46   202.6 2851.67   228.7  2837.5   269.8 2827.95
   275.2 2825.36   282.2 2824.44   291.6 2826.51   319.7 2826.52   329.1 2823.65
   343.8 2819.35   416.7 2816.69   455.12810.174   464.8  2808.9   477.82810.807
   536.9 2819.31   557.2 2821.87   567.8 2822.01   583.9 2829.73   615.9 2836.05
   629.7 2841.66   657.3  2837.5   674.4 2837.97   677.8 2838.56   682.5 2841.83
#Mann= 9 ,-1 , 0
       0     .12       0   146.1    .016       0   184.2     .12       0
   291.6    .016       0   329.1     .12       0   455.1     .04       0
   477.8     .12       0   536.9     .08       0   557.2     .12       0
Bank Sta=455.1,477.8
XS Rating Curve= 0 ,0
Exp/Cntr=0.5,0.3

Type RM Length L Ch R = 1 ,30924   ,68.9,68.9,68.9
XS GIS Cut Line= 4
      2046390.79       378278.41     2046063.983      378571.174
     2045999.303      378705.642     2045961.856      378984.789
#Sta/Elev= 30
       0 2925.85    54.1 2909.77    78.5 2881.05   113.4 2855.04   152.9 2856.34
   166.8 2859.75   177.4  2859.4   255.1 2840.11   308.6 2831.45   320.2 2825.77
   352.7  2825.2   443.8 2818.77   494.4 2811.51   506.2 2810.99   513.42809.578
   523.6 2807.19   536.1 2809.89   559.1 2815.53   571.4 2817.96   603.3 2821.01
   622.1 2820.96   635.4 2825.36   692.5 2832.44   731.3 2833.59   761.3 2834.42
   787.6 2836.89   800.8 2840.57     824 2841.51   843.9  2850.4   869.6 2851.42
#Mann= 14 ,-1 , 0
       0     .12       0   113.4    .016       0   152.9     .12       0
   308.6    .016       0   352.7     .12       0   494.4    .016       0
   506.2     .12       0   513.4     .04       0   536.1     .12       0
   559.1    .016       0   571.4     .08       0   603.3     .06       0
   692.5     .12       0   731.3     .12       0
#XS Ineff= 2 , 0
          501.66 2815.75  540.42         2817.28
Permanent Ineff=
       F       F
Bank Sta=513.4,536.1
XS Rating Curve= 0 ,0
Exp/Cntr=0.5,0.3

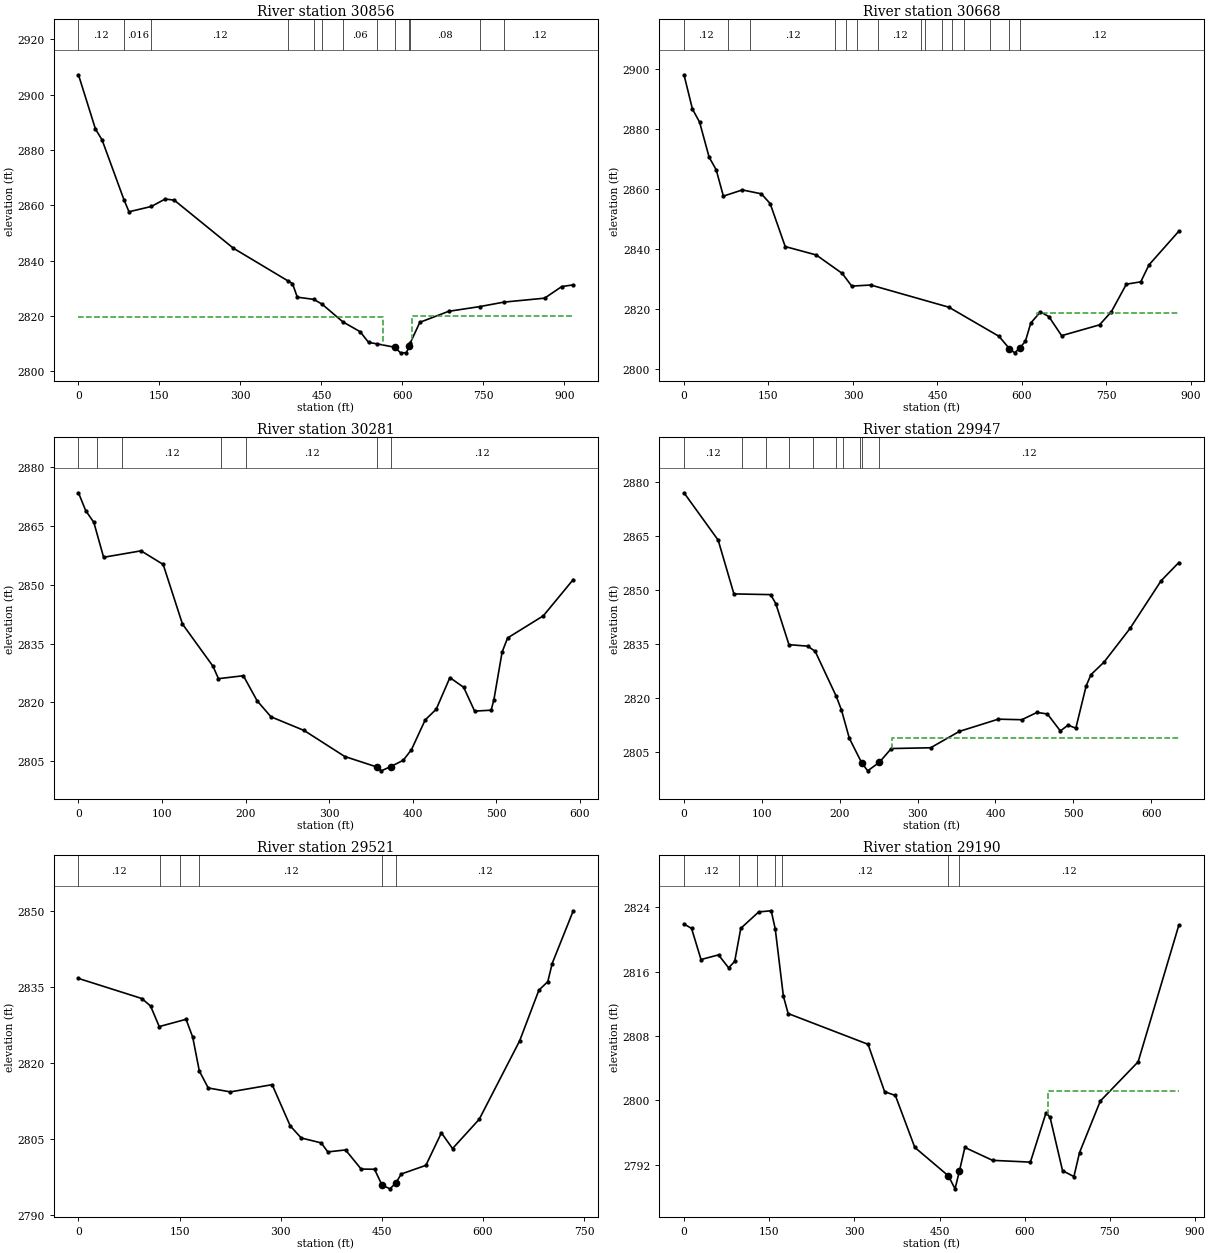
Type RM Length L Ch R = 1 ,30856   ,185.6,185.6,185.6
XS GIS Cut Line= 4
     2046297.173      378120.113     2046009.515      378516.706
     2045944.835      378668.195      2045844.41      378909.896
#Sta/Elev= 30
       0 2907.23    31.5  2887.6    43.7  2883.7    84.2 2862.09    93.6 2857.72
   135.1 2859.64   160.6 2862.33   177.4 2861.91   286.8 2844.56   388.2 2832.71
   396.3 2831.78   405.3 2826.85   435.8 2826.06   451.2 2824.32   489.5 2817.95
   521.7 2814.37   537.3 2810.49   553.8 2809.95   585.72808.748   596.6 2806.73
   607.3 2806.78   612.72809.132   614.8 2810.42   632.2 2817.75   685.6 2821.74
   743.2 2823.44   787.9 2825.06   863.3 2826.49   895.2  2830.7   916.4 2831.29
#Mann= 13 ,-1 , 0
       0     .12       0    84.2    .016       0   135.1     .12       0
   388.2    .016       0   435.8     .12       0   451.2    .016       0
   489.5     .06       0   553.8     .12       0   585.7     .04       0
   612.7     .12       0   614.8     .08       0   743.2    .016       0
   787.9     .12       0
#XS Ineff= 2 , 0
          563.68  2819.6  616.83         2820.04
Permanent Ineff=
       F       F
Bank Sta=585.7,612.7
XS Rating Curve= 0 ,0
Exp/Cntr=0.5,0.3

Type RM Length L Ch R = 1 ,30668   ,384.4,384.4,384.4
XS GIS Cut Line= 4
     2046280.152      378096.283     2045886.963      378414.579
     2045801.857      378532.025     2045597.602       378632.45
#Sta/Elev= 30
       0 2897.97      15 2886.55    27.7 2882.19    44.6 2870.53    57.2 2866.31
    69.9 2857.55   103.7 2859.62   137.4 2858.31     153 2855.06   179.7 2840.75
   234.7 2837.96     281  2831.8   297.8 2827.58   331.6 2827.94   470.3 2820.55
   559.3 2810.85   577.92806.717     587 2805.35   596.1  2806.9   606.3  2809.3
   615.7 2815.27   632.9 2819.01   647.8 2817.42   670.5 2811.07   737.8 2814.67
   758.8 2819.05   785.4 2828.21     811 2829.01   825.6 2834.65   878.5 2845.85
#Mann= 15 ,-1 , 0
       0     .12       0   78.55    .016       0  116.56     .12       0
  268.57    .016       0  287.27     .12       0  306.57    .016       0
  344.57     .12       0  420.57     .08       0   428.1    .016       0
  458.58     .08       0  475.04     .12       0  496.58     .08       0
   543.9     .12       0   577.9     .04       0   596.1     .12       0
#XS Ineff= 2 , 0
                          626.39         2818.62
Permanent Ineff=
       F       F
Bank Sta=577.9,596.1
XS Rating Curve= 0 ,0
Exp/Cntr=0.3,0.1

Type RM Length L Ch R = 1 ,30281   ,326.6,326.6,326.6
XS GIS Cut Line= 3
     2046241.003      378084.368     2045948.239      378123.517
      2045652.07      378101.389
#Sta/Elev= 30
       0 2873.38     8.7 2868.82    18.4 2865.84    30.1 2856.96    74.9  2858.6
   101.4 2855.14   124.5 2839.97     161 2829.24   167.6 2826.06   197.4 2826.81
   213.9 2820.43   230.5 2816.35   270.2 2812.87   318.8 2806.25   357.4 2803.57
   362.5  2802.6   373.7 2803.67   388.8 2805.28   398.7 2807.99   415.1 2815.56
   428.3 2818.28   444.7 2826.33   461.2 2823.86   474.3  2817.8   494.1 2818.04
   497.4 2820.73   507.2 2832.83   513.8 2836.43   556.6 2842.07   592.4  2851.3
#Mann= 7 ,-1 , 0
       0     .12       0    22.1    .016       0    51.9     .12       0
   171.1    .016       0   200.9     .12       0   357.4     .04       0
   373.7     .12       0
Bank Sta=357.4,373.7
XS Rating Curve= 0 ,0
Exp/Cntr=0.3,0.1

Type RM Length L Ch R = 1 ,29947   ,418.8,418.8,418.8
XS GIS Cut Line= 3
     2046232.493      377880.114     2045880.154      377798.412
     2045609.517      377757.561
#Sta/Elev= 30
       0 2876.98    43.9 2863.81    64.1 2848.87   111.3 2848.67   117.9 2846.16
   134.8 2834.76   158.9 2834.35   168.5  2832.9   195.5 2820.41   202.2 2816.62
   212.3 2808.75   228.12801.966   235.9 2799.69   250.92802.066   266.2 2805.89
   316.7  2806.1   353.7 2810.66   403.6 2814.05   433.9  2813.9   453.4 2815.94
   466.7 2815.49   483.3 2810.78   493.2 2812.39   503.2 2811.54   516.4 2823.27
   522.6 2826.42   539.4 2829.91   572.8 2839.28   612.7 2852.53   635.4 2857.58
#Mann= 10 ,-1 , 0
       0     .12       0   74.39    .016       0  104.71     .12       0
  135.03    .016       0  165.35     .08       0  195.67     .12       0
  204.24     .06       0  225.99     .12       0   228.1     .04       0
   250.9     .12       0
#XS Ineff= 2 , 0
                          267.19         2808.83
Permanent Ineff=
       F       F
Bank Sta=228.1,250.9
XS Rating Curve= 0 ,0
Exp/Cntr=0.3,0.1

Type RM Length L Ch R = 1 ,29521   ,319.2,319.2,319.2
XS GIS Cut Line= 4
     2046280.152       377515.86     2045878.452      377492.031
      2045699.73      377514.158     2045548.241      377512.456
#Sta/Elev= 30
       0 2836.71    93.9 2832.74     107 2831.25   119.8 2827.19   159.6 2828.63
   169.5 2825.09   179.3  2818.4   192.5 2815.06   225.3 2814.28   287.3 2815.71
   314.1 2807.57   330.5 2805.17   360.1  2804.2   369.9 2802.42   396.2 2802.81
   419.3 2799.03   439.2 2798.99   450.32795.846   462.2 2795.12   471.22796.363
   478.8 2798.05   515.3 2799.76   538.4 2806.19   554.9 2803.08   594.5 2808.87
   654.5 2824.38     683 2834.39   696.2 2836.07   702.7 2839.65     734 2850.08
#Mann= 6 ,-1 , 0
       0     .12       0  120.33    .016       0  149.92     .08       0
  179.51     .12       0   450.3     .04       0   471.2     .12       0
Bank Sta=450.3,471.2
XS Rating Curve= 0 ,0
Exp/Cntr=0.3,0.1

Type RM Length L Ch R = 1 ,29190   ,331.5,331.5,331.5
XS GIS Cut Line= 4
      2046278.45      377429.052     2045951.643      377289.478
     2045825.686      377149.905     2045502.284      377095.437
#Sta/Elev= 30
       0 2821.93    13.3 2821.38      30 2817.51    60.8 2818.09    78.6 2816.48
    89.3 2817.28     100 2821.39   131.6 2823.43   153.6 2823.57   160.7 2821.31
     175 2812.97   183.4  2810.8   324.1 2806.98   353.3 2801.09   372.2 2800.62
   406.4 2794.17   465.6 2790.63   477.3 2789.02     4852791.233   494.6 2794.16
   543.4 2792.56     610 2792.34   637.5 2798.47   644.6 2797.91   666.6 2791.28
   686.6 2790.54   696.5 2793.52   733.1 2799.93   799.7  2804.8   871.3 2821.76
#Mann= 7 ,-1 , 0
       0     .12       0   96.65    .016       0  128.77     .08       0
  160.89     .06       0  172.28     .12       0   465.6     .04       0
     485     .12       0
#XS Ineff= 2 , 0
                           641.2         2801.19
Permanent Ineff=
       F       F
Bank Sta=465.6,485
XS Rating Curve= 0 ,0
Exp/Cntr=0.3,0.1

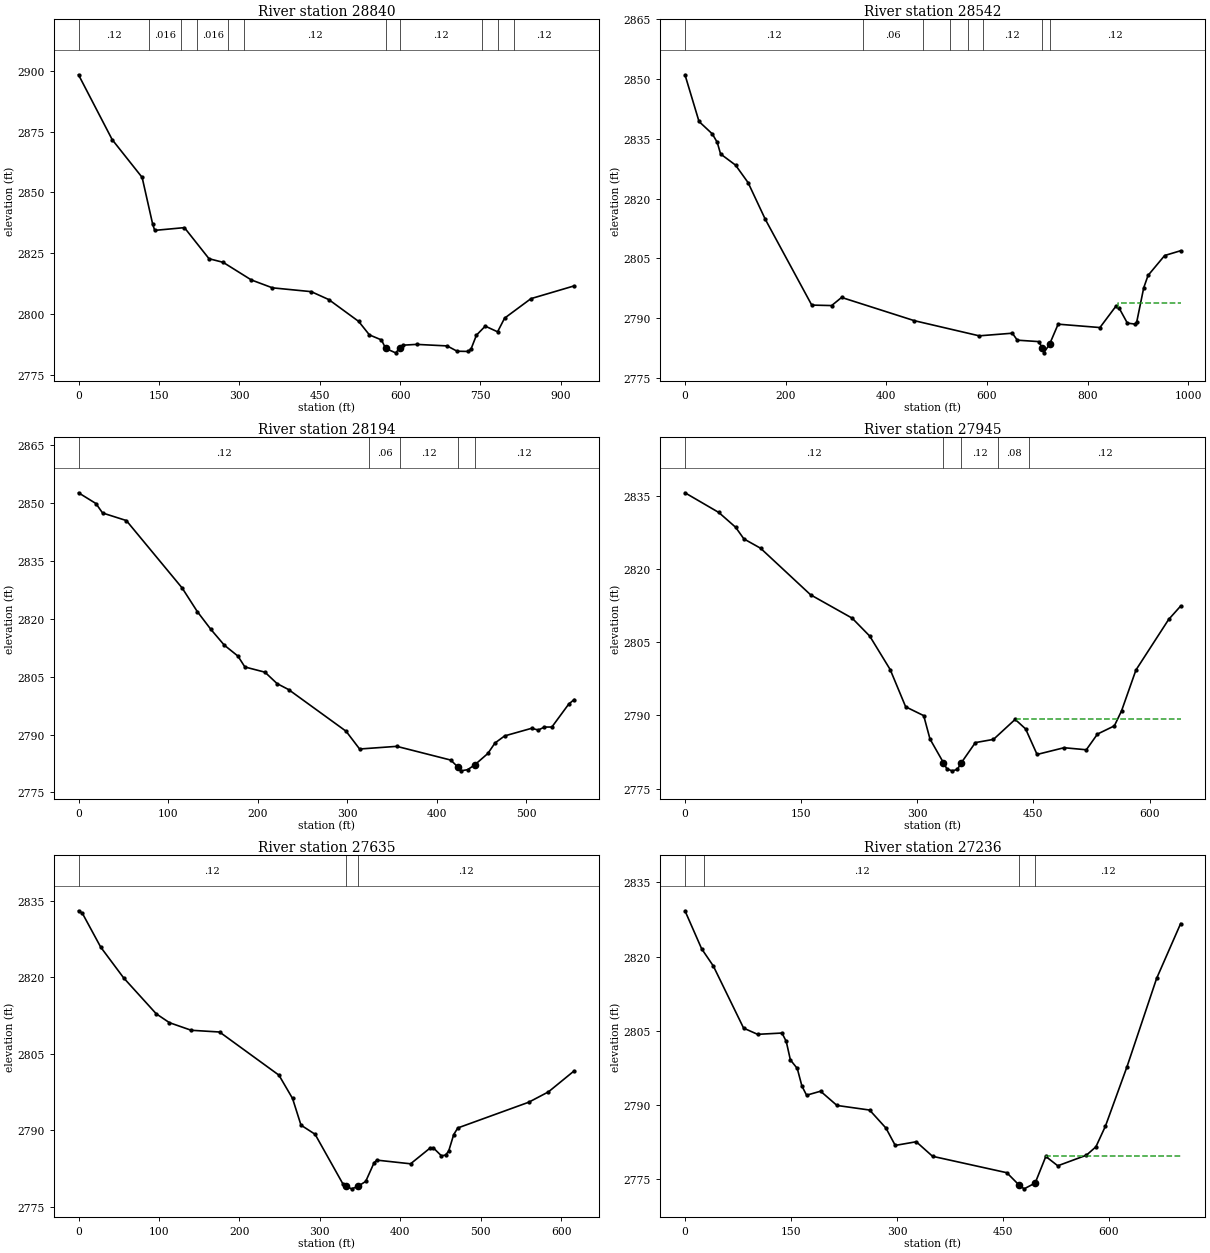
Type RM Length L Ch R = 1 ,28840   ,289.8,289.8,289.8
XS GIS Cut Line= 3
     2046469.087      376938.842     2045961.856      376915.012
     2045544.837       376913.31
#Sta/Elev= 30
       0 2898.45    62.9 2871.73   118.7 2856.21   138.4 2836.92   142.2  2834.4
   197.6 2835.53   243.5 2822.74   269.8 2821.25   322.4    2814   361.8 2810.75
   434.2 2809.18   466.9 2805.92   522.7 2796.93   542.8 2791.37   565.3  2789.3
     5732785.825   591.6 2783.99     5992785.792   604.7 2787.13     631 2787.47
   687.8 2786.84   706.4 2784.66   727.3 2784.56   732.7 2785.76   742.5 2791.28
   758.9 2794.98   781.9 2792.65     795 2798.27   844.2  2806.3   924.8 2811.55
#Mann= 11 ,-1 , 0
       0     .12       0  131.98    .016       0  191.11     .12       0
  220.68    .016       0  279.82     .08       0  309.39     .12       0
     573     .04       0     599     .12       0  752.67     .08       0
  782.21     .06       0  811.74     .12       0
Bank Sta=573,599
XS Rating Curve= 0 ,0
Exp/Cntr=0.3,0.1

Type RM Length L Ch R = 1 ,28542   ,338.7,338.7,338.7
XS GIS Cut Line= 4
     2046453.768      376637.567     2045780.808      376694.627
     2045686.504      376689.664     2045484.246      376761.633
#Sta/Elev= 30
       0 2851.07    27.9 2839.34    54.3 2836.22    64.1  2834.1    70.7 2831.19
   100.4 2828.39   125.3    2824   159.6 2814.76   251.8 2793.24   291.3 2793.12
   311.1 2795.16   455.7 2789.32   584.4 2785.52   650.2 2786.18   660.1 2784.43
   702.8 2784.07   709.22782.582   712.7 2781.25   724.2 2783.42   741.2 2788.45
   824.2  2787.6   855.6  2792.9   862.5 2792.45   878.7 2788.71   894.1 2788.47
   897.3    2789   911.2 2797.59   919.8 2800.69   952.8 2805.69   984.5 2806.89
#Mann= 8 ,-1 , 0
       0     .12       0  354.08     .06       0  472.64     .08       0
  526.31     .12       0  561.57     .06       0  591.21     .12       0
   709.2     .04       0   724.2     .12       0
#XS Ineff= 2 , 0
                          860.87         2793.88
Permanent Ineff=
       F       F
Bank Sta=709.2,724.2
XS Rating Curve= 0 ,0
Exp/Cntr=0.3,0.1

Type RM Length L Ch R = 1 ,28194   ,248.2,248.2,248.2
XS GIS Cut Line= 3
     2045743.583      376163.545     2045554.975      376494.851
     2045470.597      376644.993
#Sta/Elev= 30
       0 2852.69    19.4 2849.91    26.9 2847.45    53.4 2845.49   115.8 2827.98
   132.6  2821.9   147.7  2817.3   162.8 2813.18     178 2810.35   185.8 2807.52
   208.2 2806.17   221.7 2803.22   234.6 2801.66   298.8 2790.86   313.9 2786.25
   355.4 2786.94   415.7 2783.38   423.5 2781.61     427 2780.59   434.5 2780.89
   442.32782.106   457.1 2785.09   465.1 2787.81   475.9 2789.65     506 2791.62
   513.5 2791.17   520.2 2791.94   528.6 2791.95   547.4 2797.89   553.5 2799.08
#Mann= 5 ,-1 , 0
       0     .12       0  324.71     .06       0   358.7     .12       0
   423.5     .04       0   442.3     .12       0
Bank Sta=423.5,442.3
XS Rating Curve= 0 ,0
Exp/Cntr=0.3,0.1

Type RM Length L Ch R = 1 ,27945   ,300.9,300.9,300.9
XS GIS Cut Line= 4
     2045419.722      376123.838     2045319.214      376352.154
     2045290.675        376508.5     2045131.846      376677.255
#Sta/Elev= 30
       0 2835.65    43.7 2831.61    65.4 2828.58    76.1 2826.19    97.6 2824.28
   162.2 2814.73   215.9 2809.94   238.6 2806.26     265  2799.4     285 2791.76
   308.3 2789.95   316.4 2785.16   333.82780.297   338.3 2779.02     345 2778.63
   351.7 2778.91   356.52780.202     375 2784.42   398.4 2785.08   426.4 2789.18
   439.9 2787.23   454.7 2781.99   489.5 2783.37   518.3 2782.95   532.7 2786.17
   554.5 2787.85   563.8 2790.93   582.4 2799.31   624.6 2809.67   640.1 2812.42
#Mann= 5 ,-1 , 0
       0     .12       0   333.8     .04       0   356.5     .12       0
  404.63     .08       0  443.88     .12       0
#XS Ineff= 2 , 0
                          428.55         2789.17
Permanent Ineff=
       F       F
Bank Sta=333.8,356.5
XS Rating Curve= 0 ,0
Exp/Cntr=0.3,0.1

Type RM Length L Ch R = 1 ,27635   ,390.7,390.7,390.7
XS GIS Cut Line= 3
     2045399.869      376139.969     2045186.444       376272.74
      2044843.97      376398.065
#Sta/Elev= 30
       0 2833.08     4.8 2832.59    27.6 2825.95    56.1 2819.92    96.6 2812.88
     113 2811.14   140.1 2809.65   175.3 2809.31   249.1 2800.85     266 2796.28
   276.5 2791.05     294 2789.26   328.9 2779.44   331.9 2779.13   339.4 2778.56
   346.9 2779.02   356.9 2780.01   367.3 2783.66   370.8 2784.19   412.7 2783.47
   437.2 2786.59   440.8 2786.62     451 2785.04   456.1 2785.18     460 2785.94
   466.3  2789.2   471.4  2790.5   559.5 2795.54     584 2797.57     616 2801.69
#Mann= 3 ,-1 , 0
       0     .12       0   331.9     .04       0   346.9     .12       0
Bank Sta=331.9,346.9
XS Rating Curve= 0 ,0
Exp/Cntr=0.3,0.1

Type RM Length L Ch R = 1 ,27236   ,385.6,385.6,385.6
XS GIS Cut Line= 3
     2045360.162      375943.916     2044935.793      375991.068
     2044669.011      376055.592
#Sta/Elev= 30
       0 2829.26    23.6 2821.57    40.1  2818.1      83 2805.53   102.8 2804.28
   137.3 2804.54   143.3 2802.85   149.2  2799.1   158.9 2797.39   165.5 2793.82
   172.1 2791.97   191.9 2792.78   215.1  2789.9   261.3 2788.97   284.4 2785.33
   297.6 2781.82   327.3 2782.56   350.4 2779.62   455.5  2776.3   472.72773.824
     480 2773.04   495.62774.213   510.7 2779.59   527.6  2777.7   568.1 2779.84
   581.6 2781.54   595.1 2785.73   625.5 2797.69   667.5 2815.58   701.5 2826.67
#Mann= 4 ,-1 , 0
       0     .06       0   27.32     .12       0   472.7     .04       0
   495.6     .12       0
#XS Ineff= 2 , 0
                          510.57         2779.65
Permanent Ineff=
       F       F
Bank Sta=472.7,495.6
XS Rating Curve= 0 ,0
Exp/Cntr=0.3,0.1

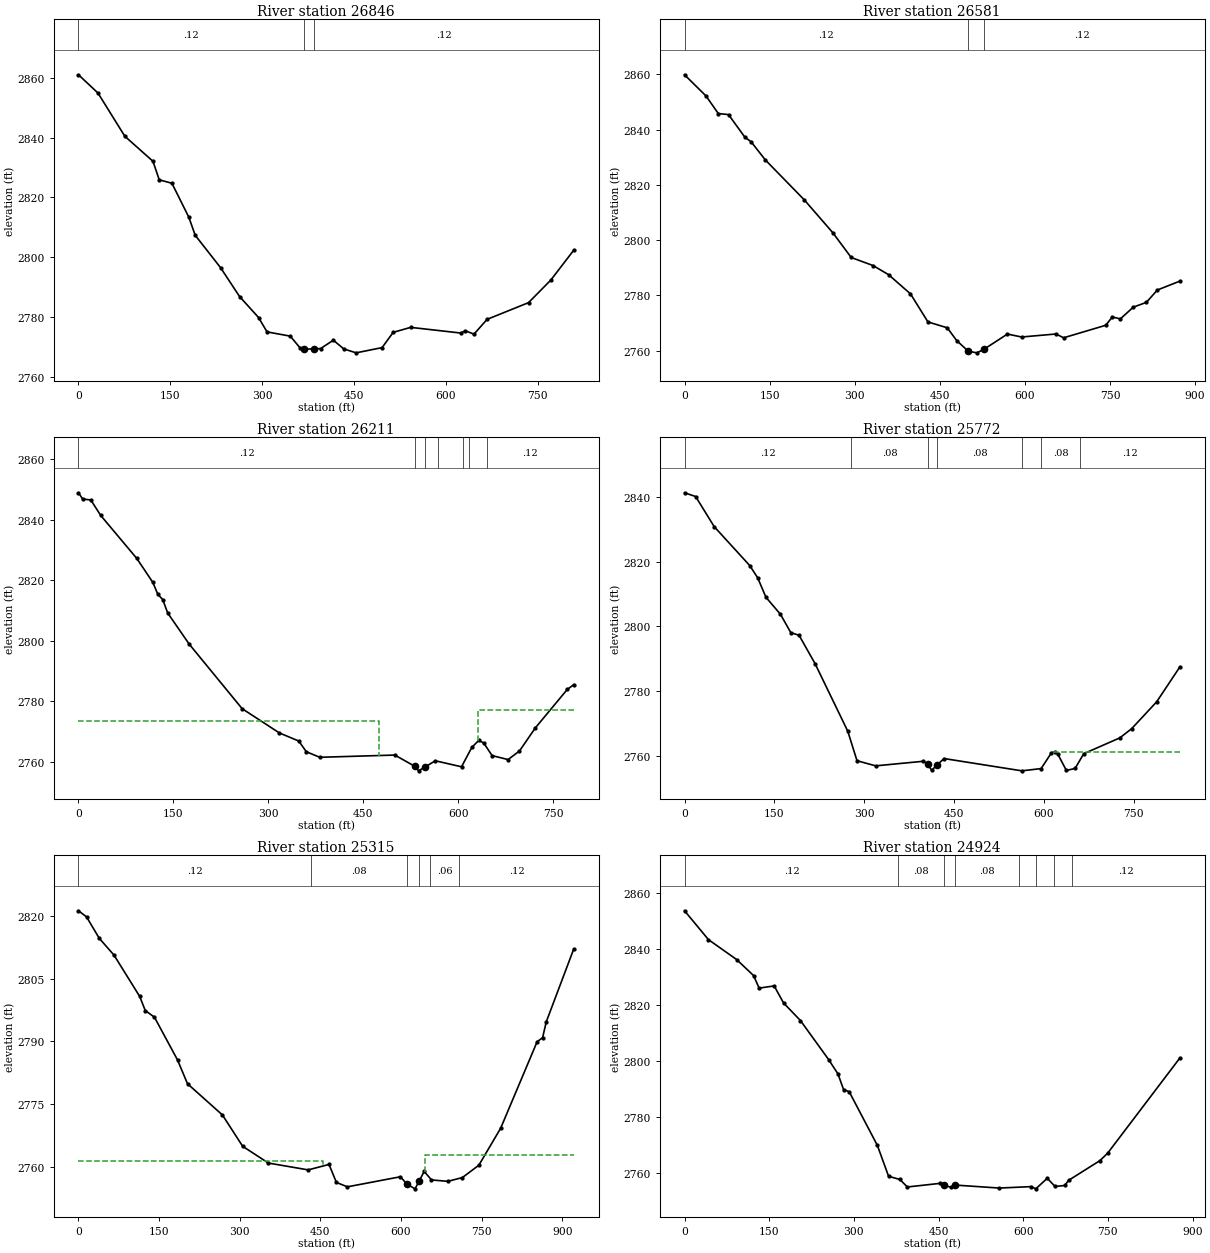
Type RM Length L Ch R = 1 ,26846   ,262.6,262.6,262.6
XS GIS Cut Line= 4
     2045334.104      375570.422     2045001.558      375679.616
     2044941.997      375726.768     2044589.597       375876.91
#Sta/Elev= 30
       0 2860.99    31.8 2854.89    75.7 2840.42   121.6 2832.06   131.9 2825.85
   152.6  2824.7   180.3 2813.31   190.6 2807.31   232.1 2796.45   263.1 2786.81
   294.1 2779.79     308 2774.97   345.9 2773.56   361.9 2769.63   368.92769.173
   383.92769.311   395.4 2769.39   416.3  2772.2   433.4 2769.27   453.5 2767.97
   495.9 2769.72     514 2774.82   542.6 2776.49   624.6 2774.59   631.7 2775.35
     646 2774.22   667.4 2779.17   735.1 2784.76   771.4 2792.29     809 2802.32
#Mann= 3 ,-1 , 0
       0     .12       0   368.9     .04       0   383.9     .12       0
Bank Sta=368.9,383.9
XS Rating Curve= 0 ,0
Exp/Cntr=0.3,0.1

Type RM Length L Ch R = 1 ,26581   ,364.6,364.6,364.6
XS GIS Cut Line= 4
     2045259.653      375282.546     2044836.525      375474.876
     2044742.221      375558.013     2044539.963      375755.307
#Sta/Elev= 30
       0  2859.8    37.9 2852.12    59.5 2845.78    77.5  2845.4   106.4  2837.2
   117.2  2835.6   142.4    2829   210.9 2814.59   261.3 2802.68   293.8  2793.7
   332.4 2790.78   359.7 2787.48   398.3 2780.54   429.1 2770.39   463.1 2768.27
   479.9 2763.61   500.22759.793   515.3 2759.21   527.22760.423   569.2    2766
   594.2 2764.94   654.9 2766.03   668.2 2764.65   742.5 2769.18   754.1 2772.18
   768.3 2771.49   791.1 2775.74   814.2 2777.47   833.4 2781.93   873.1 2785.15
#Mann= 3 ,-1 , 0
       0     .12       0   500.2     .04       0   527.2     .12       0
Bank Sta=500.2,527.2
XS Rating Curve= 0 ,0
Exp/Cntr=0.3,0.1

Type RM Length L Ch R = 1 ,26211   ,435,435,435
XS GIS Cut Line= 4
     2044762.075      375025.691      2044490.33      375441.374
     2044399.748      375560.495      2044343.91      375684.579
#Sta/Elev= 30
       0 2848.97     6.6 2846.89    19.4  2846.6    35.1 2841.47      92 2827.27
   117.4 2819.33   125.3 2815.38   133.1 2813.62   140.9  2809.2   174.9 2798.89
   258.5 2777.54   317.3 2769.52     348 2766.83   359.8 2763.31   381.1 2761.46
   499.6  2762.2   531.62758.432   537.1 2756.98   546.62758.154   563.6 2760.31
     605 2758.32   621.3 2764.74   632.2 2767.05   640.1 2766.19   653.3 2762.02
   678.5 2760.71   696.5 2763.54   721.6 2771.19     772  2783.9   782.3 2785.49
#Mann= 7 ,-1 , 0
       0     .12       0   531.6     .04       0   546.6     .12       0
  568.37     .08       0  608.06     .12       0  617.17     .08       0
  645.17     .12       0
#XS Ineff= 2 , 0
          473.98 2773.32  630.79         2777.02
Permanent Ineff=
       F       F
Bank Sta=531.6,546.6
XS Rating Curve= 0 ,0
Exp/Cntr=0.3,0.1

Type RM Length L Ch R = 1 ,25772   ,445,445,445
XS GIS Cut Line= 4
       2044711.2      375000.874     2044383.617      375108.827
     2044274.423      375146.053     2043940.635      375297.436
#Sta/Elev= 30
       0 2841.24    18.5 2840.09    49.5 2830.79   108.8 2818.79   122.1    2815
   135.9 2808.99   160.1 2803.75   177.4 2798.09   191.2 2797.26   217.9 2788.51
   272.5 2767.66   287.9 2758.56     319 2756.98   398.6 2758.39   405.82757.565
   412.5 2755.59   421.82757.331   433.3 2759.23   563.1 2755.44   595.3 2756.14
   612.3 2760.96   617.6 2761.36   623.2 2760.57   637.4 2755.55     652 2756.19
   666.4 2760.72   726.7 2765.62   746.5 2768.47   788.1 2776.73   826.8 2787.49
#Mann= 7 ,-1 , 0
       0     .12       0  278.28     .08       0   405.8     .04       0
   421.8     .08       0  562.78     .06       0  595.21     .08       0
  660.08     .12       0
#XS Ineff= 2 , 0
                           615.6         2761.26
Permanent Ineff=
       F       F
Bank Sta=405.8,421.8
XS Rating Curve= 0 ,0
Exp/Cntr=0.3,0.1

Type RM Length L Ch R = 1 ,25315   ,373.3,373.3,373.3
XS GIS Cut Line= 3
     2044655.362      374729.129     2044135.448      374881.753
     2043768.158      374977.298
#Sta/Elev= 30
       0 2821.19      15 2819.73    38.7  2814.6    66.1 2810.59   113.9 2800.71
   124.2 2797.35   141.3 2795.76   184.2 2785.55   202.8 2779.85   267.8 2772.39
   305.4 2764.91   353.3  2760.9   427.3 2759.27   466.1 2760.57   479.8 2756.27
   500.3 2755.22     599 2757.63   610.62755.906   626.1 2754.74   633.52756.543
   643.1  2758.9   656.7 2756.87   687.1 2756.53   714.2 2757.44   744.8 2760.38
   785.4 2769.23   853.2 2789.89   863.4 2790.86   870.2 2794.64   921.4 2812.08
#Mann= 6 ,-1 , 0
       0     .12       0  431.68     .08       0   610.6     .04       0
   633.5     .08       0  653.23     .06       0  708.35     .12       0
#XS Ineff= 2 , 0
          455.43 2761.47  644.52         2762.92
Permanent Ineff=
       F       F
Bank Sta=610.6,633.5
XS Rating Curve= 0 ,0
Exp/Cntr=0.3,0.1

Type RM Length L Ch R = 1 ,24924   ,305,305,305
XS GIS Cut Line= 4
     2044584.634      374533.075     2044195.009      374596.358
     2043953.044      374660.882     2043732.173      374732.851
#Sta/Elev= 30
       0  2853.5    42.4 2843.22    92.3 2836.13   122.2 2830.44   132.2 2825.96
   158.8 2826.74   175.4 2820.67   205.3 2814.42   255.2 2800.53   271.8 2795.41
   281.7 2789.84   291.7 2789.07   341.6 2769.95   361.5 2758.94   381.5 2757.81
   394.7 2755.13   453.2 2756.43   459.82755.735     472 2755.04   479.32755.813
   557.7 2754.75   614.1 2755.26   622.3 2754.47   642.6 2758.23   656.4 2755.33
   673.6 2755.66   680.5 2757.51   735.8  2764.5   749.6 2767.16   877.5 2801.05
#Mann= 8 ,-1 , 0
       0     .12       0  378.92     .08       0   459.8     .04       0
   479.3     .08       0  592.57     .06       0  623.13     .08       0
  653.84     .06       0  685.86     .12       0
Bank Sta=459.8,479.3
XS Rating Curve= 0 ,0
Exp/Cntr=0.3,0.1

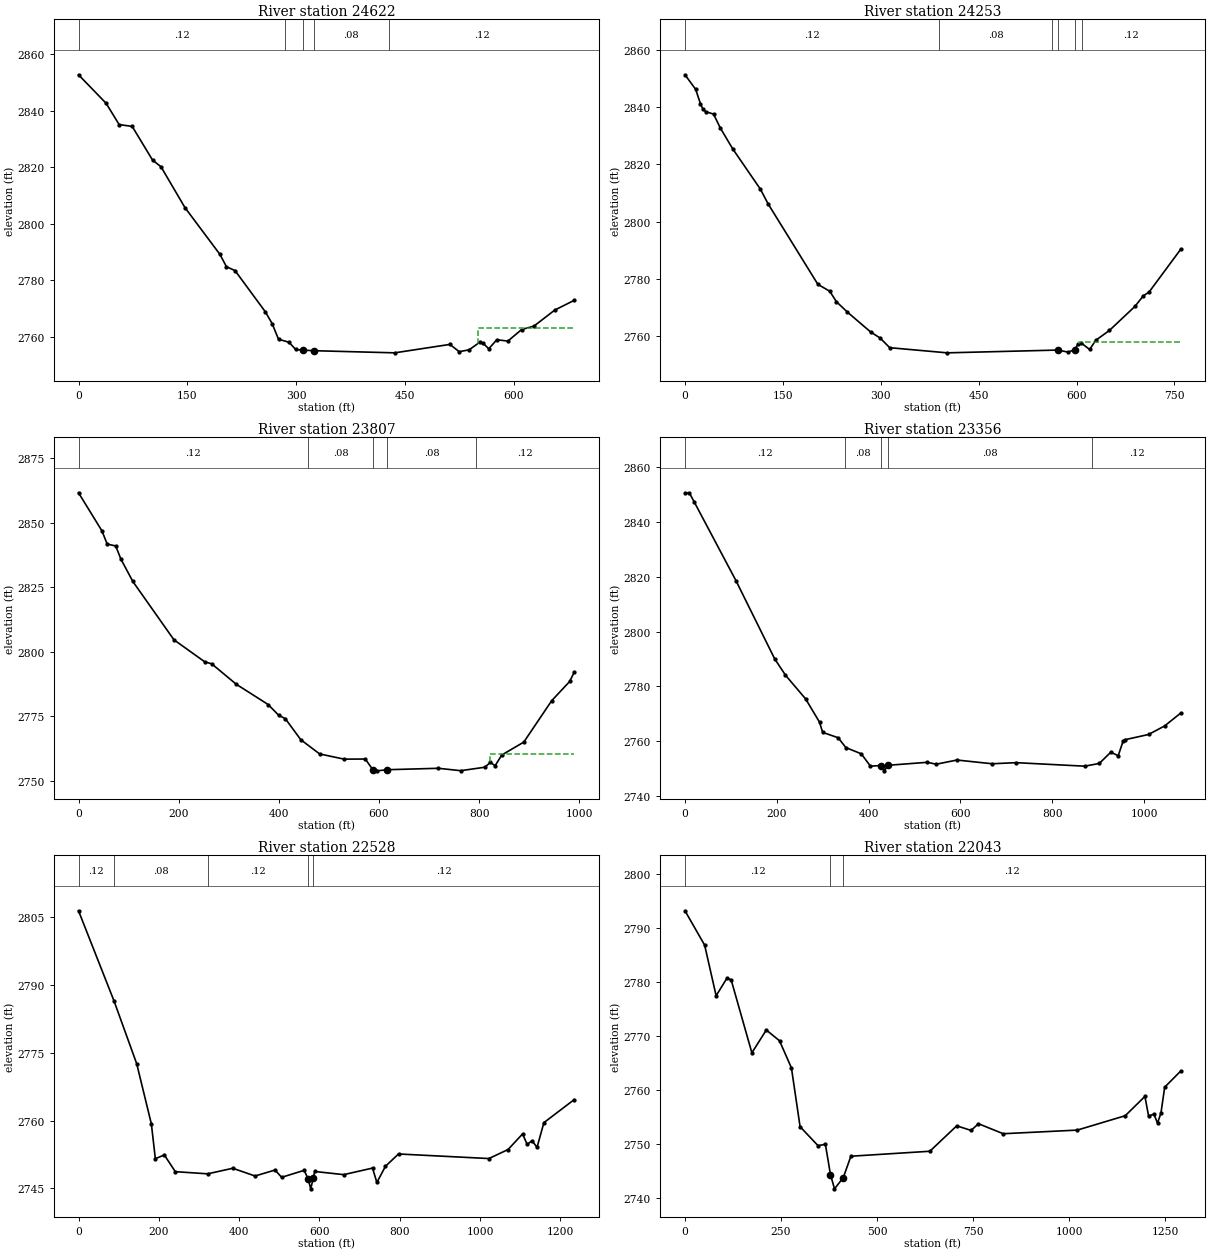
Type RM Length L Ch R = 1 ,24622   ,366.6,366.6,366.6
XS GIS Cut Line= 4
     2044291.794      374154.618     2044096.982      374335.781
     2044022.531       374407.75     2043752.027      374566.578
#Sta/Elev= 30
       0 2852.64    38.1 2842.55      56 2835.05      74  2834.4   102.1 2822.49
   113.7 2820.14   146.7 2805.73     195 2789.17   203.9 2784.85   215.8 2783.46
   257.6 2768.89   266.9 2764.76   275.7 2759.22   290.1 2758.16   299.4 2755.59
   309.32755.356   324.32755.167   435.9 2754.41     512 2757.39   524.8 2754.82
   538.6 2755.48     553 2758.15   557.7 2757.84   565.5 2755.84   576.7 2759.04
   591.9 2758.56   610.9 2762.65   627.8 2763.84   656.6 2769.53   683.3 2772.95
#Mann= 5 ,-1 , 0
       0     .12       0  284.46     .08       0   309.3     .04       0
   324.3     .08       0  427.74     .12       0
#XS Ineff= 2 , 0
                          550.39         2763.09
Permanent Ineff=
       F       F
Bank Sta=309.3,324.3
XS Rating Curve= 0 ,0
Exp/Cntr=0.3,0.1

Type RM Length L Ch R = 1 ,24253   ,445.7,445.7,445.7
XS GIS Cut Line= 3
      2044226.03      374026.811     2043768.158      374256.367
      2043580.79      374417.677
#Sta/Elev= 30
       0 2851.29    16.4 2846.19    23.7 2841.17    27.4 2839.35    31.5 2838.39
    43.7 2837.57    54.3 2832.63      73 2825.45   115.5 2811.33   127.5 2806.12
   203.6 2778.05   221.9 2775.62   231.9 2772.01     249 2768.32   284.3 2761.43
     299 2759.28   313.7 2755.91   401.7 2754.11   570.82755.077   587.4 2754.35
   596.8 2755.24   602.7 2757.27     607 2757.57     620 2755.28   629.3 2758.48
   650.3 2761.94   689.3 2770.32   702.3 2774.06   710.9  2775.3   759.4 2790.27
#Mann= 6 ,-1 , 0
       0     .12       0  388.44     .08       0     563     .08       0
   570.8     .04       0   596.8     .08       0  608.27     .12       0
#XS Ineff= 2 , 0
                          604.18         2757.79
Permanent Ineff=
       F       F
Bank Sta=570.8,596.8
XS Rating Curve= 0 ,0
Exp/Cntr=0.3,0.1

Type RM Length L Ch R = 1 ,23807   ,443.9,443.9,443.9
XS GIS Cut Line= 4
     2044177.637      373724.044     2043708.597      373863.019
     2043459.188      374014.402      2043315.25      374165.785
#Sta/Elev= 30
       0 2861.66    46.9 2846.84    57.2 2841.76    74.3 2841.02    84.6 2835.94
   108.5 2827.23   190.6  2804.6   252.2 2796.04   265.9 2795.29   315.2 2787.33
   378.8 2779.47   399.7 2775.32   413.1 2773.97   443.9 2765.82   481.5 2760.31
   530.4 2758.29   572.7 2758.33   587.52754.258   595.7 2753.75     6172754.189
   718.5 2754.74   763.2 2753.81   810.9 2755.14   822.6    2757     832 2755.75
   845.2 2759.89   889.2  2764.9   944.8 2780.94     981 2788.47   989.8 2792.01
#Mann= 5 ,-1 , 0
       0     .12       0   458.5     .08       0   587.5     .04       0
     617     .08       0  793.75     .12       0
#XS Ineff= 2 , 0
                          822.65         2760.17
Permanent Ineff=
       F       F
Bank Sta=587.5,617
XS Rating Curve= 0 ,0
Exp/Cntr=0.3,0.1

Type RM Length L Ch R = 1 ,23356   ,816.6,816.6,816.6
XS GIS Cut Line= 4
      2043945.17       373410.48     2043591.129      373495.586
     2043414.109      373526.224     2042908.579      373703.245
#Sta/Elev= 30
       0 2850.59     9.6 2850.51    19.8 2847.35   110.9  2818.6   195.2 2790.09
   218.8 2784.11   262.7 2775.46   293.1 2766.94   299.8 2763.25   333.6  2761.3
   350.4  2757.7   383.9 2755.44   403.9 2750.93   426.22751.167   433.9 2749.23
   442.52751.258   527.7 2752.34   547.2 2751.65   592.4 2753.17   668.9 2751.81
     721 2752.21   870.5 2750.93   902.2 2751.92   927.3 2756.02   943.5 2754.75
   953.9 2759.95   957.4 2760.55  1009.5 2762.48  1044.3 2765.57  1079.4 2770.26
#Mann= 5 ,-1 , 0
       0     .12       0  348.83     .08       0   426.2     .04       0
   442.5     .08       0  887.11     .12       0
Bank Sta=426.2,442.5
XS Rating Curve= 0 ,0
Exp/Cntr=0.3,0.1

Type RM Length L Ch R = 1 ,22528   ,490.2,490.2,490.2
XS GIS Cut Line= 4
     2043666.022       372976.44     2043153.684      373046.227
     2043009.004      373054.737     2042486.454      373287.927
#Sta/Elev= 30
       0 2806.41    88.4 2786.47   144.9 2772.58   181.4 2759.27   191.3 2751.58
   213.7  2752.4     241 2748.71   321.6 2748.23   384.1 2749.46   439.6 2747.75
   489.3 2749.07   505.8 2747.46   561.8    2749   571.82747.129   578.2 2744.91
   584.7  2747.3   588.1 2748.75   660.4 2748.05   732.1  2749.5   742.9 2746.32
   764.4 2749.91   796.8 2752.62  1021.9 2751.61  1069.5  2753.6  1105.7 2757.05
  1117.1 2754.75  1129.6 2755.56  1141.7 2754.07  1158.8 2759.55  1234.2 2764.64
#Mann= 5 ,-1 , 0
       0     .12       0    88.4     .08       0   321.6     .12       0
   571.8     .04       0   584.7     .12       0
Bank Sta=571.8,584.7
XS Rating Curve= 0 ,0
Exp/Cntr=0.5,0.3

Type RM Length L Ch R = 1 ,22043   ,66,66,66
XS GIS Cut Line= 4
 2043504.6169374372515.6997808022043177.23964478372618.796497263
2043104.89107183 372664.014355362042491.73691603373269.933653858
#Sta/Elev= 30
       0 2793.13    51.2 2786.78    81.1 2777.42   109.2 2780.66   120.2 2780.37
   174.2 2766.87   211.8 2771.09   246.2 2769.09   277.2 2764.08   299.7 2753.21
   346.5  2749.7   365.6 2749.96   378.82744.371   389.3 2741.72   412.1 2743.78
     432 2747.75   637.6 2748.67   707.6 2753.37     745 2752.52   764.1 2753.76
   828.6 2751.91  1021.4 2752.58  1146.4 2755.24  1197.6 2758.81  1207.1  2755.2
  1221.1 2755.53  1230.4 2753.86  1239.4 2755.75  1249.1 2760.52  1290.6 2763.48
#Mann= 3 ,-1 , 0
       0     .12       0   378.8     .04       0   412.1     .12       0
Bank Sta=378.8,412.1
XS Rating Curve= 0 ,0
Exp/Cntr(USF)=0,0
Exp/Cntr=0.5,0.3