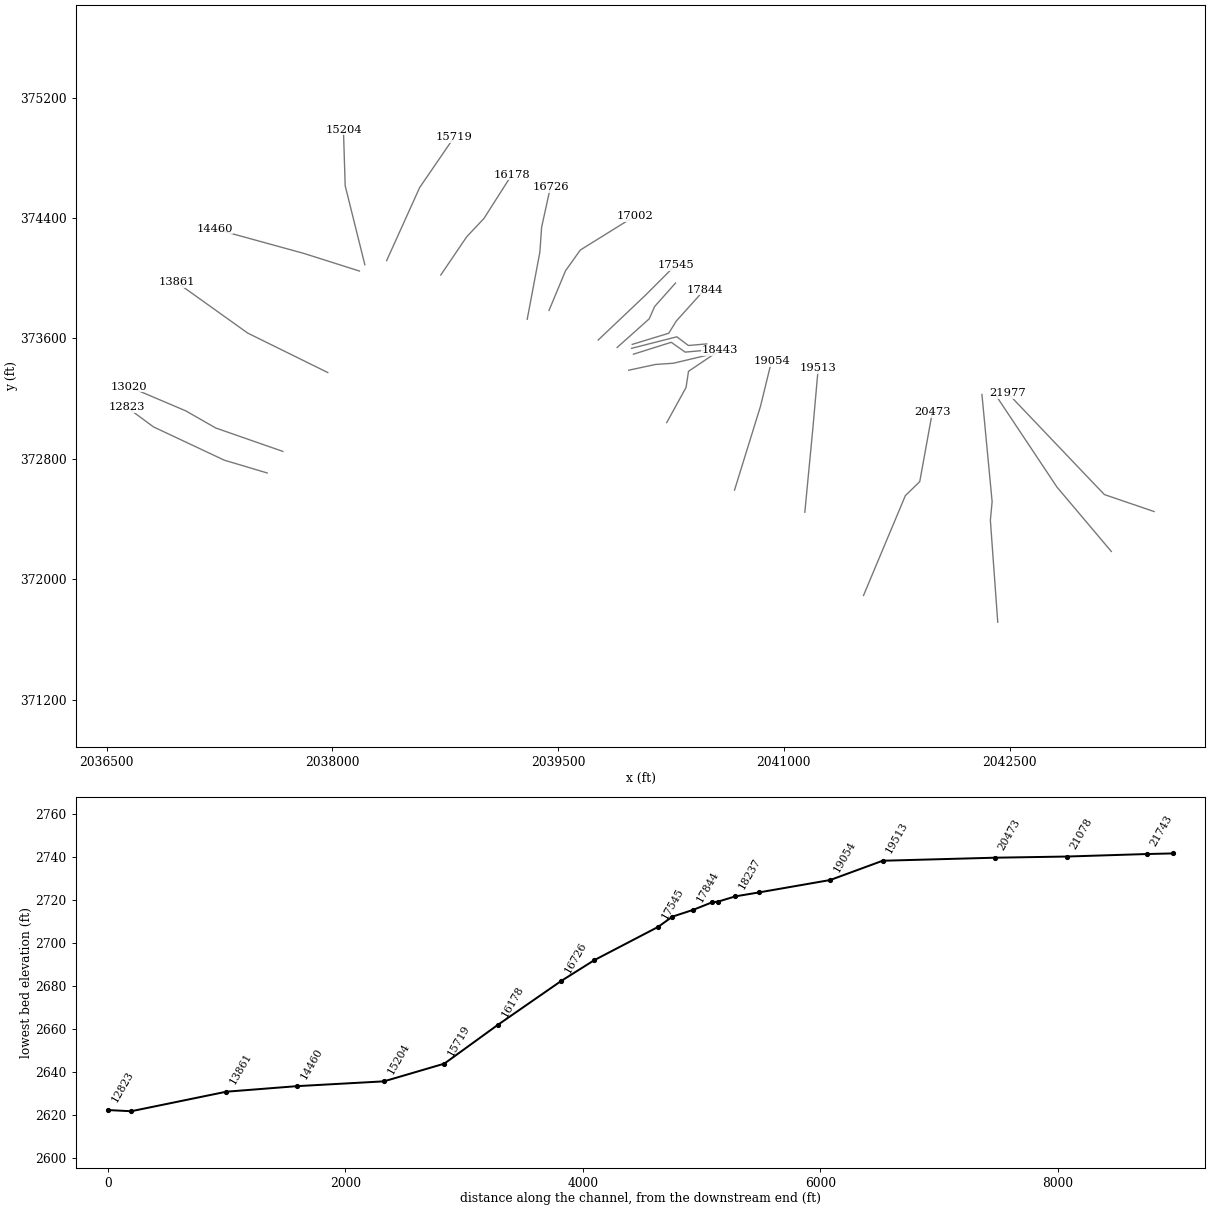
HEC-RAS study MEADOWCK2.prj: MEADOWCK2

--- MEADOWCK2.g01 (geometry) --- (continued)

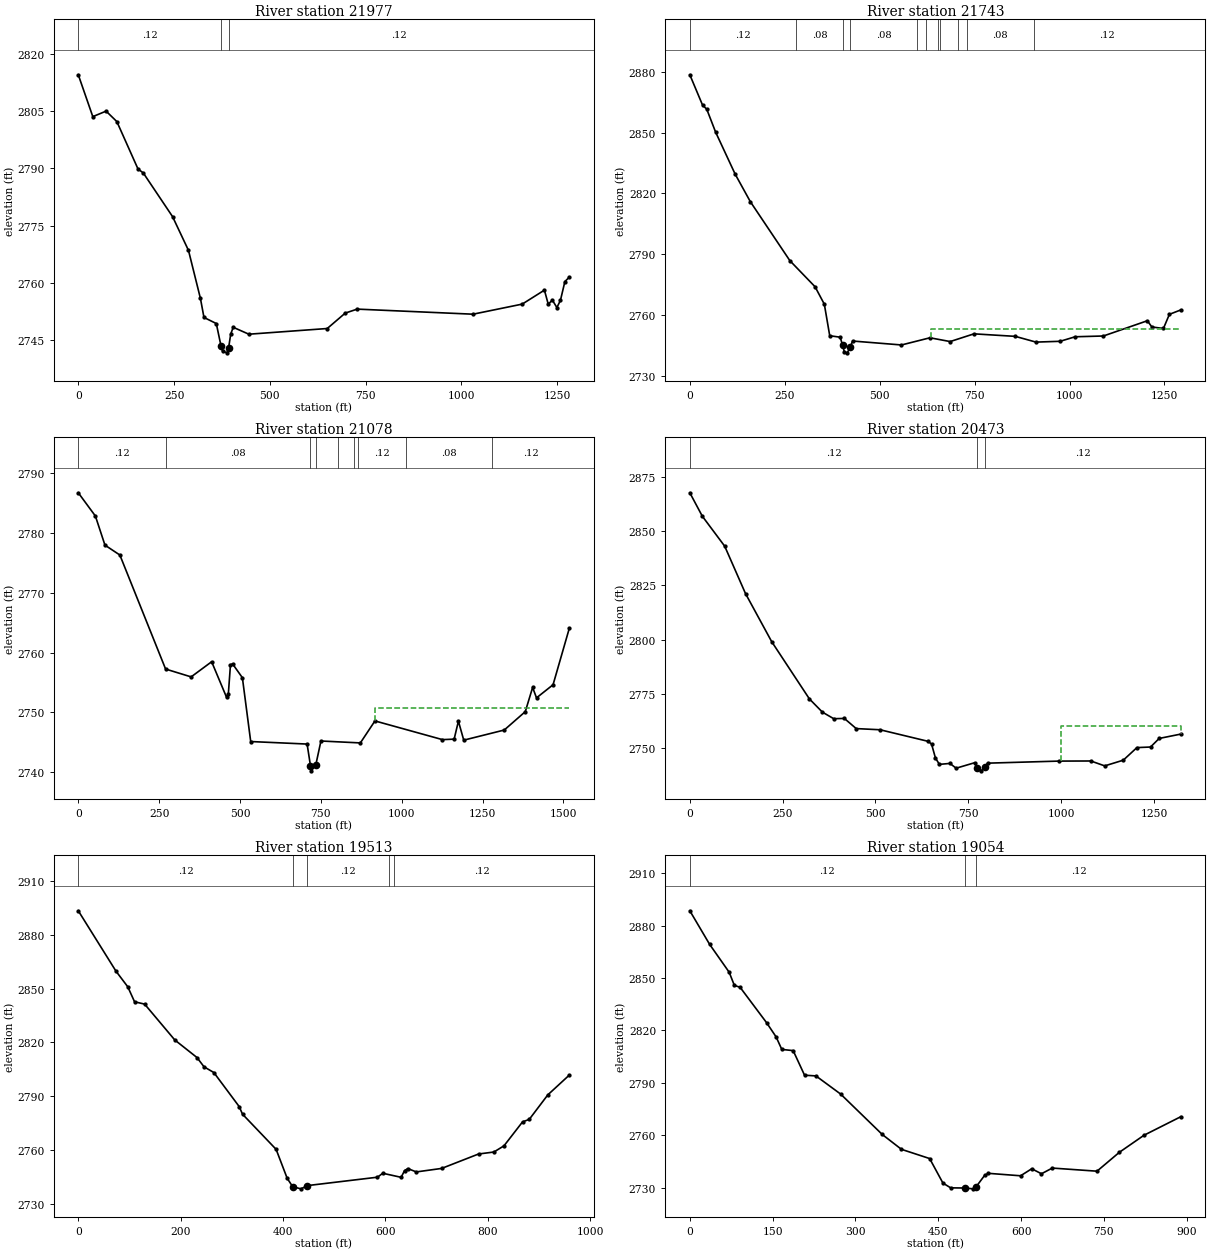
Type RM Length L Ch R = 1 ,21977   ,224.6,224.6,224.6
XS GIS Cut Line= 4
2043459.90149995372450.1841286262043130.31355649372562.726353223
2043074.04244419372621.0071481032042486.21028893373237.979700803
#Sta/Elev= 30
       0 2814.53    37.9 2803.57    72.6 2805.01   100.6 2802.28   155.8 2789.87
   169.7 2788.81     246 2777.39   287.6 2768.54   318.8 2755.95     328 2750.98
   360.2 2749.38   372.62743.459   376.5 2742.12   388.1 2741.71   392.4 2743.09
   397.8  2746.6   404.3  2748.4   445.2 2746.59   649.7 2748.08   696.7 2752.12
   727.9 2753.16  1030.2 2751.83  1158.5 2754.47  1216.5 2758.13  1226.4 2754.48
  1237.4  2755.5    1249 2753.57  1258.3 2755.45  1269.9 2760.37  1281.5 2761.55
#Mann= 3 ,-1 , 0
       0     .12       0   372.6     .04       0   392.4     .12       0
Bank Sta=372.6,392.4
XS Rating Curve= 0 ,0
Exp/Cntr(USF)=0,0
Exp/Cntr=0.5,0.3

Type RM Length L Ch R = 1 ,21743   ,674.4,674.4,674.4
XS GIS Cut Line= 3
     2043175.812      372184.954     2042814.963      372612.186
     2042408.156      373223.247
#Sta/Elev= 30
       0 2878.46    33.6 2863.49    44.6  2861.5    67.9 2850.22   119.4  2829.5
   159.4 2815.92   263.5 2786.85   329.9 2773.98   354.3 2765.38   368.5 2749.84
   396.2 2749.13   402.22745.138   407.2 2741.81   414.8 2741.42   421.92744.092
   428.8 2747.24   557.5  2745.3   632.5 2748.84   685.7 2746.98   748.4 2750.78
   857.2 2749.54   911.7 2746.71   975.4 2747.11  1014.8 2749.34  1089.2 2749.72
  1205.1 2757.24  1216.9 2754.17  1247.4 2753.43  1263.1  2760.4  1293.3 2762.58
#Mann= 11 ,-1 , 0
       0     .12       0  280.35     .08       0   402.2     .04       0
   421.9     .08       0  599.12     .12       0  622.64     .08       0
  652.43     .12       0  658.12     .08       0  705.73     .12       0
  729.09     .08       0  906.51     .12       0
#XS Ineff= 2 , 0
                          635.66         2752.96
Permanent Ineff=
       F       F
Bank Sta=402.2,421.9
XS Rating Curve= 0 ,0
Exp/Cntr=0.3,0.1

Type RM Length L Ch R = 1 ,21078   ,603.9,603.9,603.9
XS GIS Cut Line= 4
     2042421.255       371714.91     2042372.223      372392.022
     2042383.897       372515.77     2042316.186      373227.905
#Sta/Elev= 30
       0 2786.66    52.9 2782.78    82.5 2777.92   128.6 2776.27     270 2757.24
     349 2755.93   412.4 2758.46   458.4 2752.54   464.1 2753.12   470.6 2757.95
   477.2  2758.1   507.5 2755.79   533.2 2745.14   707.6 2744.72   718.12741.081
   720.7 2740.25   734.52741.245   750.4 2745.23   872.3 2744.91   917.4 2748.58
  1126.1 2745.46  1162.3 2745.54  1175.5 2748.54    1192 2745.37  1317.2 2747.06
  1382.3 2750.13    1405 2754.17    1417 2752.43  1468.2 2754.62  1518.5 2764.05
#Mann= 9 ,-1 , 0
       0     .12       0  271.41     .08       0   718.1     .04       0
   734.5     .08       0  804.69     .12       0  851.35     .08       0
  864.03     .12       0 1012.39     .08       0 1279.42     .12       0
#XS Ineff= 2 , 0
                          917.83         2750.71
Permanent Ineff=
       F       F
Bank Sta=718.1,734.5
XS Rating Curve= 0 ,0
Exp/Cntr=0.3,0.1

Type RM Length L Ch R = 1 ,20473   ,945.9,945.9,945.9
XS GIS Cut Line= 4
     2041529.335       371892.36     2041807.184      372555.463
     2041902.914      372648.858     2041986.969      373111.162
#Sta/Elev= 30
       0 2867.52    33.7 2856.74      94 2842.96     150 2821.19   220.5 2799.09
   322.1 2772.77   357.2 2766.68   387.7 2763.67   416.2  2763.8   448.2 2759.13
   512.6 2758.59   640.9 2753.31     651 2752.08   661.6  2745.6   672.3 2742.68
   700.6 2743.12   717.3 2740.92     767 2743.43   774.4 2741.03   785.5 2739.71
     7942741.417   801.8 2743.24   994.1 2744.19  1080.1 2744.24  1117.5 2741.99
  1167.5 2744.61  1204.2 2750.39  1240.9 2750.66  1264.2  2754.6  1322.6 2756.61
#Mann= 3 ,-1 , 0
       0     .12       0   774.4     .04       0     794     .12       0
#XS Ineff= 2 , 0
                          998.45         2760.36
Permanent Ineff=
       F       F
Bank Sta=774.4,794
XS Rating Curve= 0 ,0
Exp/Cntr=0.3,0.1

Type RM Length L Ch R = 1 ,19513   ,441.3,441.3,441.3
XS GIS Cut Line= 3
     2041139.412      372445.724     2041193.114      373006.092
     2041228.137      373400.685
#Sta/Elev= 30
       0 2893.53    73.6 2859.83    96.7 2851.07   109.9 2842.72   129.6 2841.42
   188.5  2821.4   231.8 2811.61   245.6 2806.42   264.8 2803.22   314.2 2784.25
   320.8 2779.96   386.4 2760.34     408 2744.18   418.92739.441   435.1 2738.29
   447.2 2740.09   584.4 2744.79   594.7 2746.99   630.6 2744.72   637.2 2748.44
   643.7 2749.61   660.2 2747.73   709.7 2749.69   781.8 2757.74   811.7 2758.84
   831.5 2762.31   867.7 2775.66   880.9 2777.09   917.1 2790.76   959.1 2801.81
#Mann= 5 ,-1 , 0
       0     .12       0   418.9     .04       0   447.2     .12       0
  605.94     .08       0  616.51     .12       0
Bank Sta=418.9,447.2
XS Rating Curve= 0 ,0
Exp/Cntr=0.3,0.1

Type RM Length L Ch R = 1 ,19054   ,600.9,600.9,600.9
XS GIS Cut Line= 3
     2040672.438      372592.821     2040845.219      373150.854
       2040917.6      373447.383
#Sta/Elev= 30
       0 2888.44      36 2869.16    71.3 2853.27    80.7 2845.72      91 2844.68
   139.1 2824.37   156.3 2816.26   166.6  2809.1   187.2 2808.41   207.8 2794.34
   228.4 2793.94   273.2 2783.54   348.6 2760.41   383.3 2751.92   434.4 2746.64
   458.5 2732.59   472.5 2729.88   498.42729.783   513.4 2729.31   518.92730.628
     534 2737.03   540.9 2738.18   599.1 2736.78   619.3  2740.8   636.9 2737.94
   656.5  2741.2   737.5 2739.41     778 2750.22   822.7 2759.99   889.4 2770.61
#Mann= 3 ,-1 , 0
       0     .12       0   498.4     .04       0   518.9     .12       0
Bank Sta=498.4,518.9
XS Rating Curve= 0 ,0
Exp/Cntr=0.3,0.1

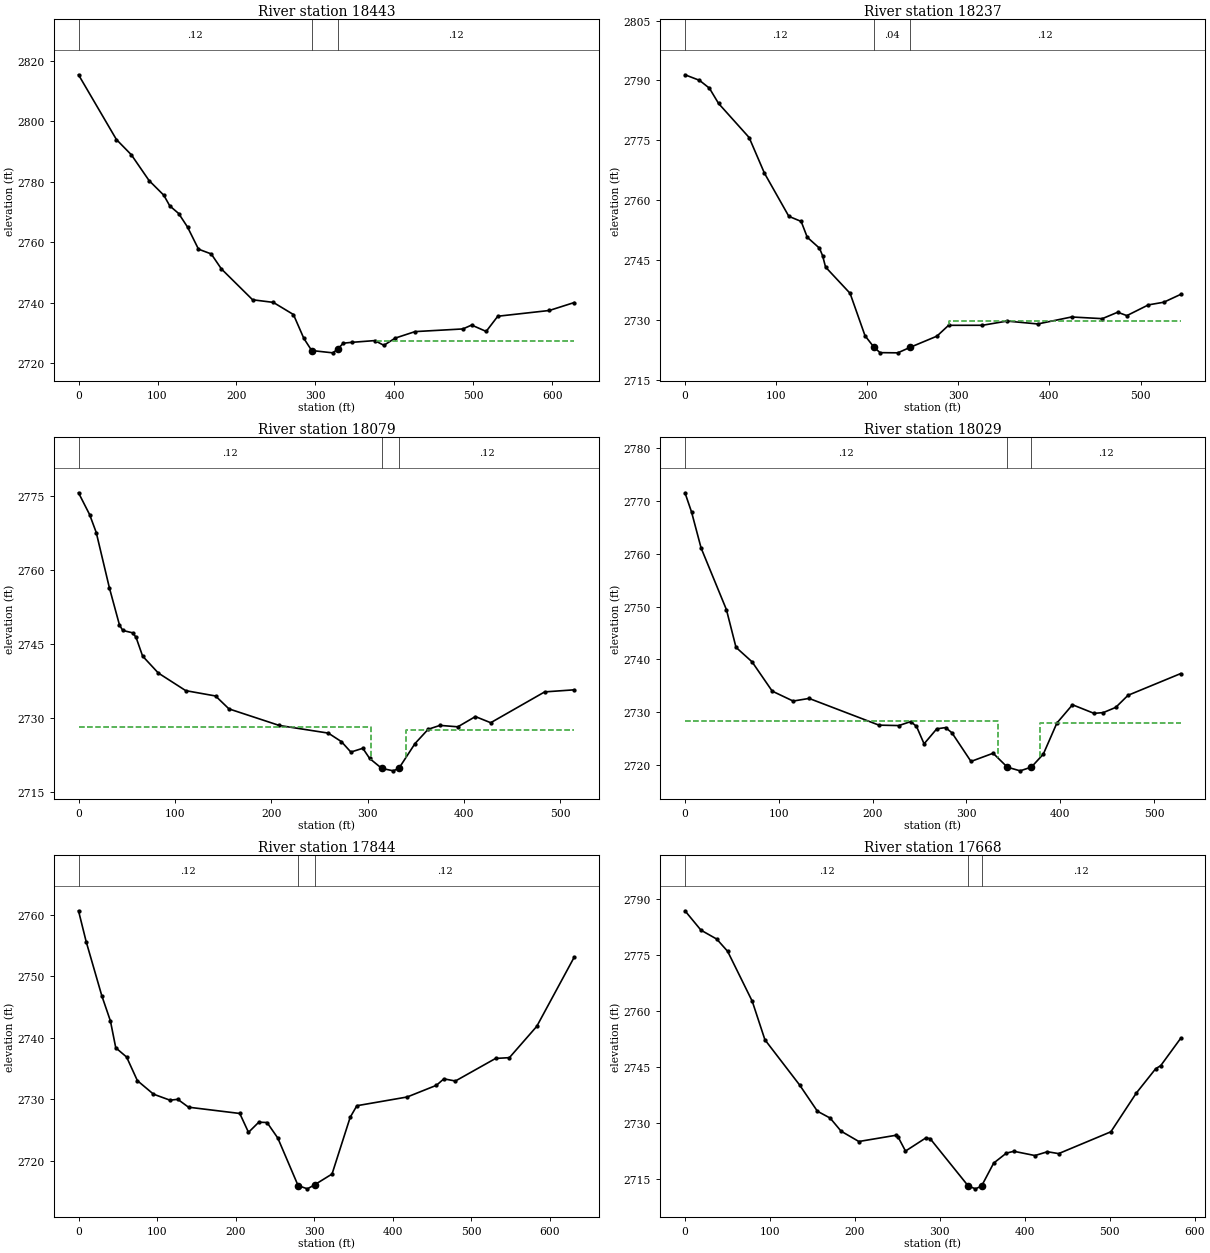
Type RM Length L Ch R = 1 ,18443   ,198.3,198.3,198.3
XS GIS Cut Line= 4
     2040221.809      373041.116     2040350.227      373274.602
     2040366.571      373382.0062040576.06741398373522.672324347
#Sta/Elev= 30
       0 2815.44      48 2794.03    66.9 2788.99    89.3 2780.48     108 2775.62
   115.5 2772.11   126.8 2769.58     138 2765.11   151.9 2757.79     168 2756.22
   180.9 2751.26   220.4 2741.06   246.6  2740.2   272.1 2736.18   285.3 2728.28
   295.2 2724.28   321.9 2723.52   328.3 2724.78   335.1  2726.7   345.9 2726.99
   375.1 2727.57   386.6    2726   400.8 2728.38   426.1 2730.54   486.6 2731.42
   497.7  2732.7   516.1  2730.6   530.8 2735.62     596 2737.52   627.5 2740.14
#Mann= 3 ,-1 , 0
       0     .12       0   295.2     .04       0   328.3     .12       0
#XS Ineff= 2 , 0
                          376.98         2727.59
Permanent Ineff=
       F       F
Bank Sta=295.2,328.3
XS Rating Curve= 0 ,0
Exp/Cntr=0.3,0.1

Type RM Length L Ch R = 1 ,18237   ,145.4,145.4,145.4
XS GIS Cut Line= 4
2039969.31847933373389.1423513722040147.56727595373427.396659322
2040266.39980703 373435.53587378 2040502.4370263373491.696453536
#Sta/Elev= 30
       0  2791.4    15.9 2790.01    26.8 2788.04    36.9  2784.2    70.4 2775.67
    87.2 2766.74     114 2755.91   127.5 2754.64   134.2 2750.67   147.6 2747.93
     151 2746.07   154.3 2743.19   181.2 2736.61   197.6 2725.98   207.5 2723.08
   214.1 2721.74   233.6 2721.69   246.9 2723.05   276.5 2725.87   289.3 2728.59
   326.5  2728.6   353.5 2729.65   387.2 2728.93   424.3 2730.68     458 2730.26
   474.9 2731.87     485 2731.02   508.6 2733.71   525.5 2734.38     544 2736.34
#Mann= 3 ,-1 , 0
       0     .12       0   207.5     .04       0   246.9     .12       0
#XS Ineff= 2 , 0
                          289.71         2729.55
Permanent Ineff=
       F       F
Bank Sta=207.5,246.9
XS Rating Curve= 0 ,0
Exp/Cntr(USF)=0,0
Exp/Cntr=0.5,0.3

Type RM Length L Ch R = 1 ,18079   ,50.2,50.2,50.2
XS GIS Cut Line= 4
2040000.94425957373495.6137979732040251.63206486 373574.56417821
2040344.41910967373509.450462551  2040481.971834373521.659284237
#Sta/Elev= 30
       0 2775.69    11.5 2771.27    18.4 2767.62    32.1 2756.34    42.5 2748.85
    45.9 2747.74    56.2 2747.25    59.7 2746.34    66.5 2742.53    82.8 2739.09
   111.3 2735.51   142.2 2734.43   156.1 2731.81   208.4 2728.44   259.2 2726.89
   272.8 2725.16   282.6 2723.04     295 2723.81   302.1 2721.74   314.7 2719.72
   326.7 2719.23   332.6 2719.79   349.2 2724.78   362.8 2727.67   375.1 2728.46
   393.6 2728.17   411.8 2730.25   427.7    2729   483.7 2735.26   514.3 2735.68
#Mann= 3 ,-1 , 0
       0     .12       0   314.7     .04       0   332.6     .12       0
#XS Ineff= 2 , 0
          303.65 2728.04  339.53         2727.53
Permanent Ineff=
       F       F
Bank Sta=314.7,332.6
XS Rating Curve= 0 ,0
Exp/Cntr(USF)=0,0
Exp/Cntr=0.5,0.3

Type RM Length L Ch R = 1 ,18029   ,157.4,157.4,157.4
XS GIS Cut Line= 4
2039988.73543788373534.6820273692040289.07245136373611.190643269
2040365.58106726373553.4022206212040487.66928412373563.983199416
#Sta/Elev= 30
       0 2771.56       7 2767.92    17.2  2761.1    44.2 2749.43    54.4  2742.3
    71.5 2739.56      93 2734.01   115.3 2732.13   132.3 2732.63   206.8 2727.57
     228 2727.49   240.6 2728.24   246.8 2727.34   254.9 2724.03   268.4 2726.87
   277.8 2727.11   284.6 2726.12   304.9  2720.7   328.5 2722.25   343.7 2719.61
   357.3 2718.92   369.3 2719.63     382 2722.08   396.5 2727.97   413.1 2731.43
   436.1  2729.8     446 2729.95   459.2 2730.93   472.3 2733.22   528.4 2737.33
#Mann= 3 ,-1 , 0
       0     .12       0   343.7     .04       0   369.3     .12       0
#XS Ineff= 2 , 0
          333.55 2728.42  378.74         2728.04
Permanent Ineff=
       F       F
Bank Sta=343.7,369.3
XS Rating Curve= 0 ,0
Exp/Cntr(USF)=0,0
Exp/Cntr=0.5,0.3

Type RM Length L Ch R = 1 ,17844   ,176.3,176.3,176.3
XS GIS Cut Line= 4
2039992.80504511373560.7275136332040235.35363594373634.794365195
2040285.00284413373715.3725883242040473.83261954373925.364321326
#Sta/Elev= 30
       0 2760.67     9.7 2755.67    29.7 2746.82    40.6 2742.75    47.4 2738.38
    61.2 2736.88    74.9 2733.04    95.4 2730.84   116.4 2729.86   126.3    2730
     140 2728.72   205.2  2727.7   216.3 2724.63   229.4 2726.28   239.9 2726.23
   253.6  2723.7   279.4 2715.97   291.3 2715.44   300.8 2716.13   322.6 2717.85
   345.7 2727.08   354.2 2728.96   418.2 2730.38   455.4 2732.28   464.9 2733.33
   479.6 2732.98   530.7 2736.65   548.3 2736.78   583.1 2741.87   630.7 2753.11
#Mann= 3 ,-1 , 0
       0     .12       0   279.4     .04       0   300.8     .12       0
Bank Sta=279.4,300.8
XS Rating Curve= 0 ,0
Exp/Cntr(USF)=0,0
Exp/Cntr=0.3,0.1

Type RM Length L Ch R = 1 ,17668   ,121.3,121.3,121.3
XS GIS Cut Line= 4
2039892.46904167373540.3927444092040105.54057203373730.501678765
2040141.31950069 373812.205799432040280.16310443373968.137846711
#Sta/Elev= 30
       0 2786.91    18.8 2781.71    37.4 2779.31    50.2 2776.03    79.2 2762.61
    94.1 2752.28     135 2740.12   155.9 2733.09   170.9 2731.25   183.8 2727.73
   204.7 2724.96     248 2726.62   251.2 2726.04   259.6 2722.39   283.2 2725.87
   288.5 2725.76   333.4 2713.04   341.9 2712.25   349.1 2712.98   363.4 2719.16
   378.4 2721.85   387.2 2722.33     412 2721.19   426.7 2722.21   439.9 2721.71
   501.4 2727.57   531.3 2737.96   554.1  2744.5   560.1 2745.34   583.5 2752.65
#Mann= 3 ,-1 , 0
       0     .12       0   333.4     .04       0   349.1     .12       0
Bank Sta=333.4,349.1
XS Rating Curve= 0 ,0
Exp/Cntr(USF)=0,0
Exp/Cntr=0.3,0.1

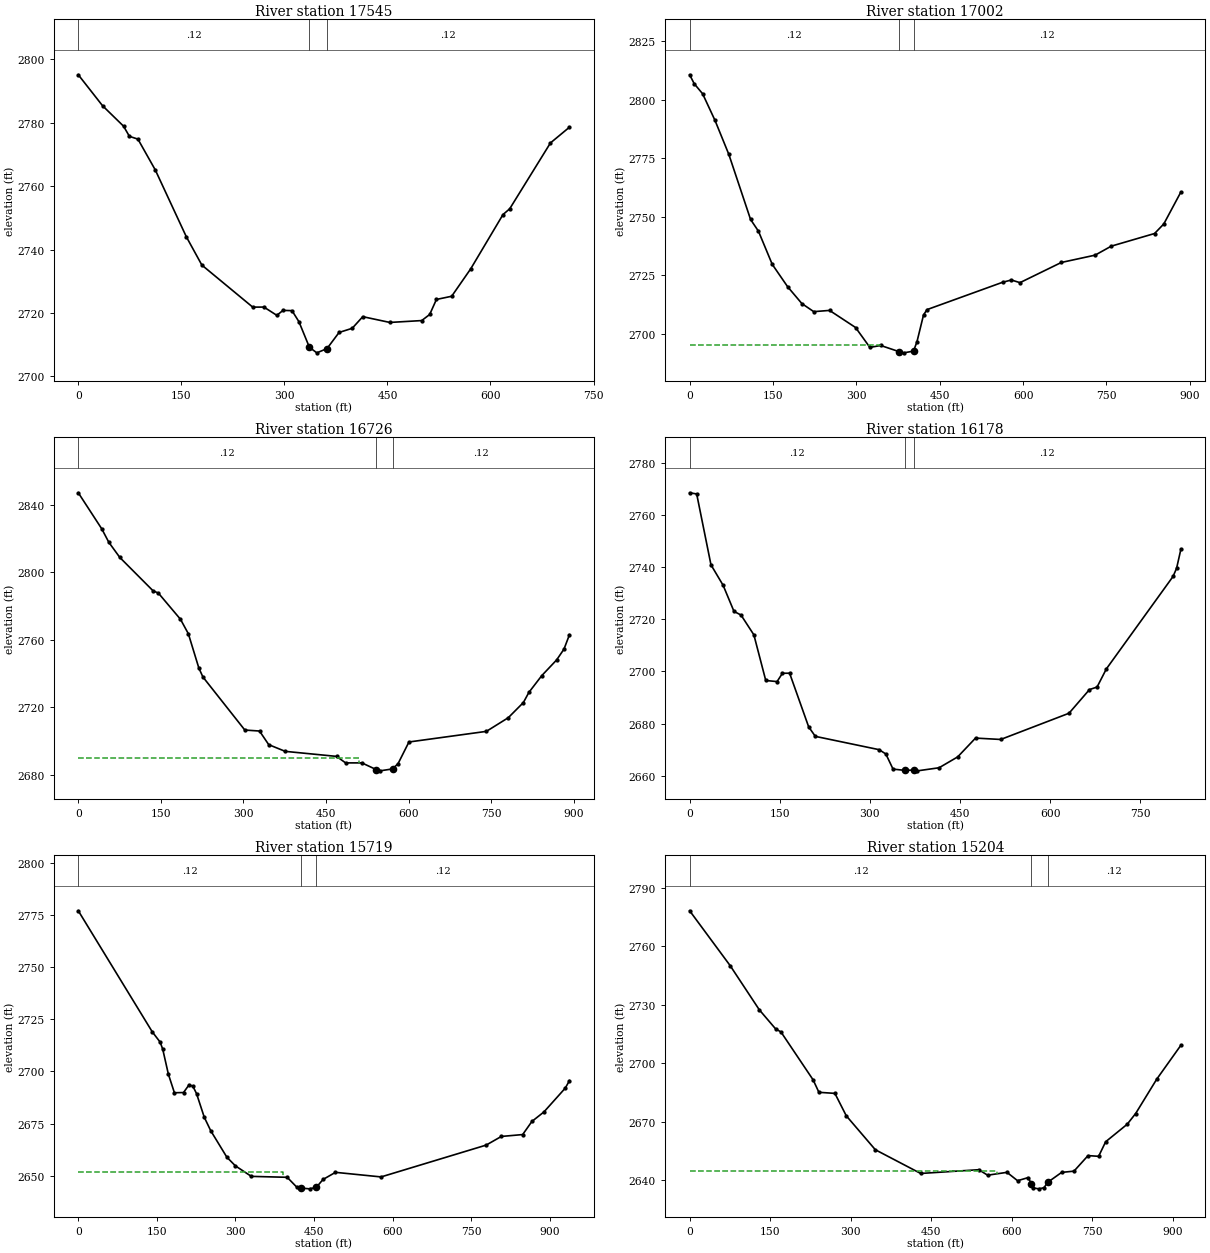
Type RM Length L Ch R = 1 ,17545   ,536.5,536.5,536.5
XS GIS Cut Line= 3
     2039766.509       373589.81     2040081.717      373888.673
      2040280.18      374087.137
#Sta/Elev= 30
       0 2795.16    35.3  2785.4    65.9 2778.94    74.4 2775.74    86.8 2774.86
   112.1 2765.13   157.3 2744.04   179.9 2735.12   253.9 2721.86   270.2 2721.88
     289 2719.27     298 2720.83   311.1 2720.75   321.2 2717.25   336.42709.201
   347.2 2707.44     3622708.771   379.6 2713.87   398.7 2715.18   414.1 2718.85
   453.5 2717.03   499.9 2717.62   511.5 2719.54   521.3 2724.28   543.5 2725.29
   571.3 2733.97   618.2 2751.06     628 2752.89   687.3 2773.66     715 2778.63
#Mann= 3 ,-1 , 0
       0     .12       0   336.4     .04       0     362     .12       0
Bank Sta=336.4,362
XS Rating Curve= 0 ,0
Exp/Cntr=0.3,0.1

Type RM Length L Ch R = 1 ,17002   ,279.4,279.4,279.4
XS GIS Cut Line= 4
     2039439.628      373785.939     2039549.367      374049.779
     2039647.431      374187.536     2040011.671      374414.018
#Sta/Elev= 30
       0 2810.72     8.2  2806.9    23.3 2802.62    45.6 2791.24    70.5 2776.72
   109.6 2748.94   123.8 2743.91   148.6 2729.76   176.3  2720.2   201.9 2713.01
   223.3 2709.56   251.7 2710.09   298.5 2702.79   324.3 2694.29   343.8 2695.11
   376.82692.482   385.5 2691.97   402.82692.717     409 2696.71   420.8 2708.15
   427.1 2710.43   563.1 2722.11   578.9 2723.08   594.3 2721.94   668.7 2730.56
   729.5 2733.69   758.6 2737.53   836.5 2742.93   853.1 2747.01   883.8 2760.63
#Mann= 3 ,-1 , 0
       0     .12       0   376.8     .04       0   402.8     .12       0
#XS Ineff= 2 , 0
          343.13 2695.48
Permanent Ineff=
       F       F
Bank Sta=376.8,402.8
XS Rating Curve= 0 ,0
Exp/Cntr=0.3,0.1

Type RM Length L Ch R = 1 ,16726   ,532.3,532.3,532.3
XS GIS Cut Line= 4
     2039294.866      373727.567     2039378.921      374173.527
     2039390.596      374339.302     2039448.967      374605.477
#Sta/Elev= 30
       0 2846.97    42.7 2825.57    55.5 2817.63    75.5 2808.64   135.6 2788.98
   145.6 2787.51   185.7 2772.02     200 2763.45   219.1  2743.1   226.5 2737.82
   302.6 2706.41   329.3 2705.83     346 2697.76     376 2693.79   469.3 2690.81
   485.7 2686.96   515.3 2686.96   541.8 2682.92   548.2 2682.25   571.12683.392
   581.1 2686.56   600.8 2699.34   741.5 2705.63   781.3 2713.73   808.7  2722.7
   818.7 2728.71   842.2 2738.68   869.1 2747.94   882.5 2754.36   892.5 2762.93
#Mann= 3 ,-1 , 0
       0     .12       0   541.8     .04       0   571.1     .12       0
#XS Ineff= 2 , 0
          510.11 2689.73
Permanent Ineff=
       F       F
Bank Sta=541.8,571.1
XS Rating Curve= 0 ,0
Exp/Cntr=0.3,0.1

Type RM Length L Ch R = 1 ,16178   ,451.6,451.6,451.6
XS GIS Cut Line= 4
     2038720.488       374021.76     2038893.269      374276.261
     2039007.677      374397.674     2039192.132      374687.198
#Sta/Elev= 30
       0 2768.64    11.7 2768.19    35.5 2740.96    55.7 2733.11    73.8 2723.08
    85.5 2721.68   106.9 2714.08   126.7 2696.54   145.5 2696.12   154.5 2699.32
   166.4 2699.34   198.1 2678.74   209.2 2675.08   315.4 2669.97   326.6 2668.31
   338.6  2662.5   357.72662.037   372.72662.119   379.2 2661.84   415.2 2663.02
   446.2  2667.2   475.9 2674.42   517.8 2673.89   631.5 2683.96   665.6 2693.06
   678.2 2694.02   693.7    2701   804.7  2736.5   810.6 2739.64   817.7 2746.89
#Mann= 3 ,-1 , 0
       0     .12       0   357.7     .04       0   372.7     .12       0
Bank Sta=357.7,372.7
XS Rating Curve= 0 ,0
Exp/Cntr=0.3,0.1

Type RM Length L Ch R = 1 ,15719   ,508.1,508.1,508.1
XS GIS Cut Line= 3
     2038360.919       374117.49     2038580.396      374603.143
     2038809.213      374937.029
#Sta/Elev= 30
       0 2776.99   141.3 2718.94   156.2 2714.06   161.2 2710.66     172 2698.65
   183.5 2689.78   200.9 2689.88   211.6 2693.63   218.8 2692.87   225.7  2689.4
   240.5 2678.03   252.9 2671.55   283.6  2658.9     300 2654.73   330.4  2649.7
   398.8 2649.26   416.8 2644.62   425.8 2644.08   441.4 2643.73   454.5 2644.48
   467.2 2648.22     491 2651.64     578 2649.44   778.6 2664.69   807.6 2668.84
   848.3 2669.74     866 2676.04   888.9 2680.58   929.5 2691.96   937.7  2695.6
#Mann= 3 ,-1 , 0
       0     .12       0   425.8     .04       0   454.5     .12       0
#XS Ineff= 2 , 0
           390.5 2651.67
Permanent Ineff=
       F       F
Bank Sta=425.8,454.5
XS Rating Curve= 0 ,0
Exp/Cntr=0.3,0.1

Type RM Length L Ch R = 1 ,15204   ,732.6,732.6,732.6
XS GIS Cut Line= 3
     2038216.157      374089.471     2038085.404      374614.817
      2038073.73      374988.396
#Sta/Elev= 30
       0 2778.19    75.4 2750.06   129.8 2727.36     160 2717.62   170.1    2716
     230 2691.42   240.8 2685.03   270.6 2684.48   291.8 2672.97   345.9 2655.56
   430.4 2643.38   538.6 2645.31   555.1 2642.49   591.2 2643.96   610.9 2639.66
   630.5 2641.25   636.8 2638.06   640.5 2635.95   650.3 2635.49   660.2 2636.06
   666.7 2638.76     693 2643.93     716 2644.57   742.2 2652.55   761.9 2652.18
     775 2659.65   815.1 2668.63   830.9 2674.15   870.2 2691.79   915.1 2709.15
#Mann= 3 , 0 , 0
       0     .12       0   636.8     .04       0   666.7     .12       0
#XS Ineff= 2 , 0
          571.74 2644.64
Permanent Ineff=
       F       F
Bank Sta=636.8,666.7
XS Rating Curve= 0 ,0
Exp/Cntr=0.3,0.1

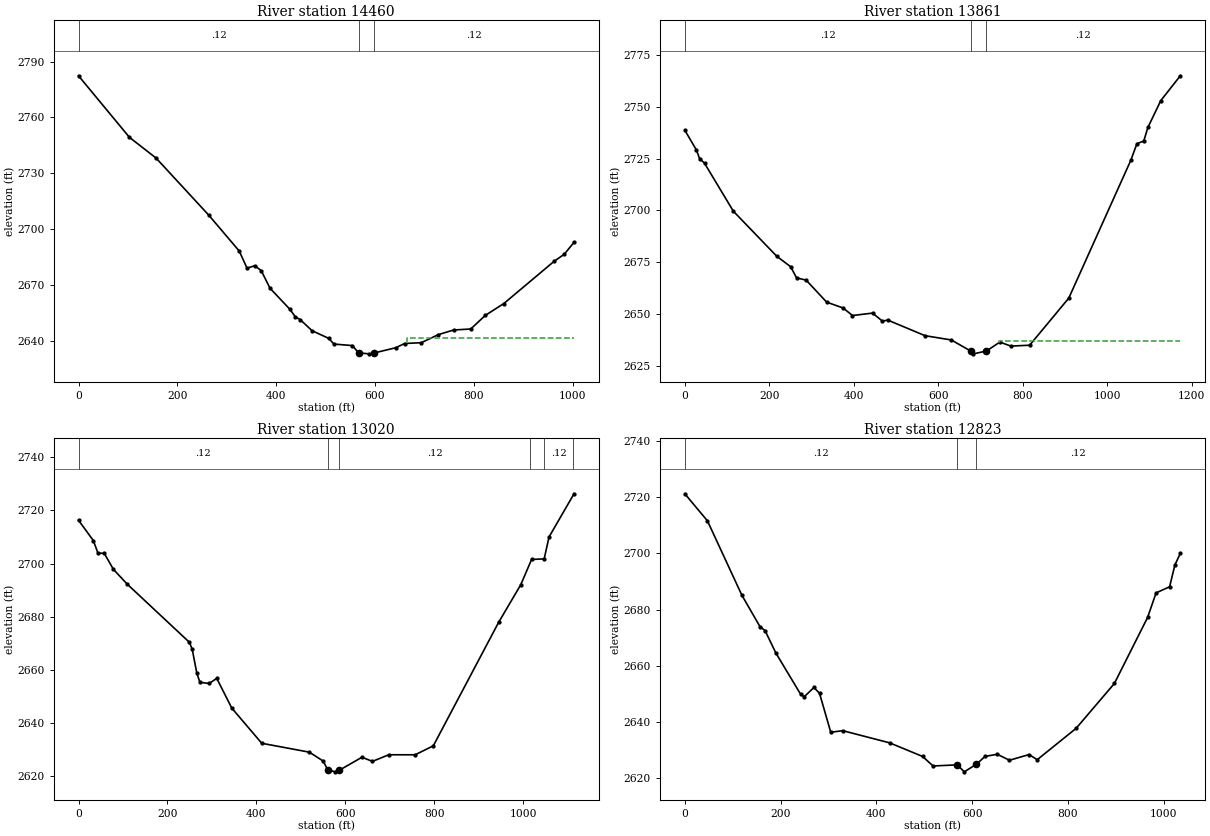
Type RM Length L Ch R = 1 ,14460   ,594.7,594.7,594.7
XS GIS Cut Line= 3
     2038179.837      374048.222     2037811.446      374164.966
     2037217.352      374328.406
#Sta/Elev= 30
       0 2782.35   103.1 2749.33   156.9 2738.24   263.6  2707.6   325.3 2688.35
     341 2679.18   356.5  2680.5   369.7 2677.87   387.4 2668.45   428.1 2657.03
   438.5 2653.13   448.7 2651.58   472.5 2645.66   506.5 2641.53   516.7 2638.49
   554.2 2637.68   566.72633.757   588.2 2633.25   598.6 2633.74   642.6 2636.57
   659.7 2638.79   693.7 2639.23   727.7 2643.51     759 2646.04   793.7 2646.57
   822.9 2653.83   860.5  2660.2   962.5 2682.91   982.9 2686.67  1002.6 2693.04
#Mann= 3 ,-1 , 0
       0     .12       0   566.7     .04       0   598.6     .12       0
#XS Ineff= 2 , 0
                          664.01         2641.56
Permanent Ineff=
       F       F
Bank Sta=566.7,598.6
XS Rating Curve= 0 ,0
Exp/Cntr=0.3,0.1

Type RM Length L Ch R = 1 ,13861   ,800.9,800.9,800.9
XS GIS Cut Line= 3
     2037969.698      373373.705     2037437.867      373635.729
     2036965.705      373972.987
#Sta/Elev= 30
       0 2738.84    27.5 2729.25    34.9 2725.11    46.6 2722.89   114.9 2699.66
   217.7 2677.86   250.6  2672.8   264.6 2667.39   287.2 2666.34   335.7 2655.68
     375 2652.82   396.9 2649.19   444.5 2650.37     468 2646.44   480.3    2647
   568.8 2639.44   630.9 2637.37   678.12631.875   683.3 2630.66   714.22632.031
   745.8 2636.33     772 2634.41   816.4 2634.83   909.1 2657.64  1055.9  2724.3
  1070.3 2732.31  1086.5 2733.61  1096.3 2740.16  1126.9 2753.19  1173.1 2765.17
#Mann= 3 ,-1 , 0
       0     .12       0   678.1     .04       0   714.2     .12       0
#XS Ineff= 2 , 0
                          743.47         2637.09
Permanent Ineff=
       F       F
Bank Sta=678.1,714.2
XS Rating Curve= 0 ,0
Exp/Cntr=0.3,0.1

Type RM Length L Ch R = 1 ,13020   ,197.4,197.4,197.4
XS GIS Cut Line= 4
     2037671.354      372849.656     2037225.135      373005.314
     2037025.374      373119.463     2036646.606       373280.31
#Sta/Elev= 30
       0 2716.31    33.3 2708.66    43.8 2703.88    57.7 2703.89    78.5 2697.81
   109.8  2692.2   249.4 2670.33   255.7 2667.71   266.1 2658.68   273.1 2655.26
   293.9 2654.85   310.9 2656.75   344.7 2645.55   412.1 2632.31   519.1 2628.97
   550.3  2625.6   560.12622.388   576.9 2621.56     5862622.111   637.3 2627.05
     661  2625.5   697.7 2627.99   756.9 2627.98   797.8 2631.36   944.5  2677.8
   994.6 2692.07  1018.8 2701.55  1047.1 2701.75    1058    2710  1114.2 2726.27
#Mann= 6 ,-1 , 0
       0     .12       0   560.1     .04       0     586     .12       0
 1015.15    .016       0 1047.24     .12       0 1111.42    .016       0
#XS Ineff= 2 , 0
                          637.65         2626.78
Permanent Ineff=
       F       F
Bank Sta=560.1,586
XS Rating Curve= 0 ,0
Exp/Cntr=0.3,0.1

Type RM Length L Ch R = 1 ,12823   ,254.6,254.6,254.6
XS GIS Cut Line= 4
2037567.01884082372706.4760642812037282.24690303372791.377014676
2036811.75413626373012.4732396612036636.64592608373141.593435053
#Sta/Elev= 30
       0 2721.28    47.2 2711.64   119.1 2685.11   156.8 2673.94   167.8 2672.41
   189.9 2664.56   241.7 2649.81   249.2 2648.89   269.7 2652.22   281.3  2650.1
   304.7 2636.23   329.8  2636.8   427.8 2632.45   496.5  2627.6   518.3 2624.21
     569 2624.61   583.5 2622.12   608.9 2624.85     627 2627.63   652.4 2628.38
   677.8 2626.25   718.8 2628.28   735.8 2626.45     817 2637.63   896.9 2653.63
   966.2 2677.16     984 2685.94  1012.2 2688.11  1023.2 2695.87  1034.6 2700.05
#Mann= 3 , 0 , 0
       0     .12       0     569     .04       0   608.9     .12       0
Bank Sta=569,608.9
XS Rating Curve= 0 ,0
Exp/Cntr(USF)=0,0
Exp/Cntr=0.3,0.1