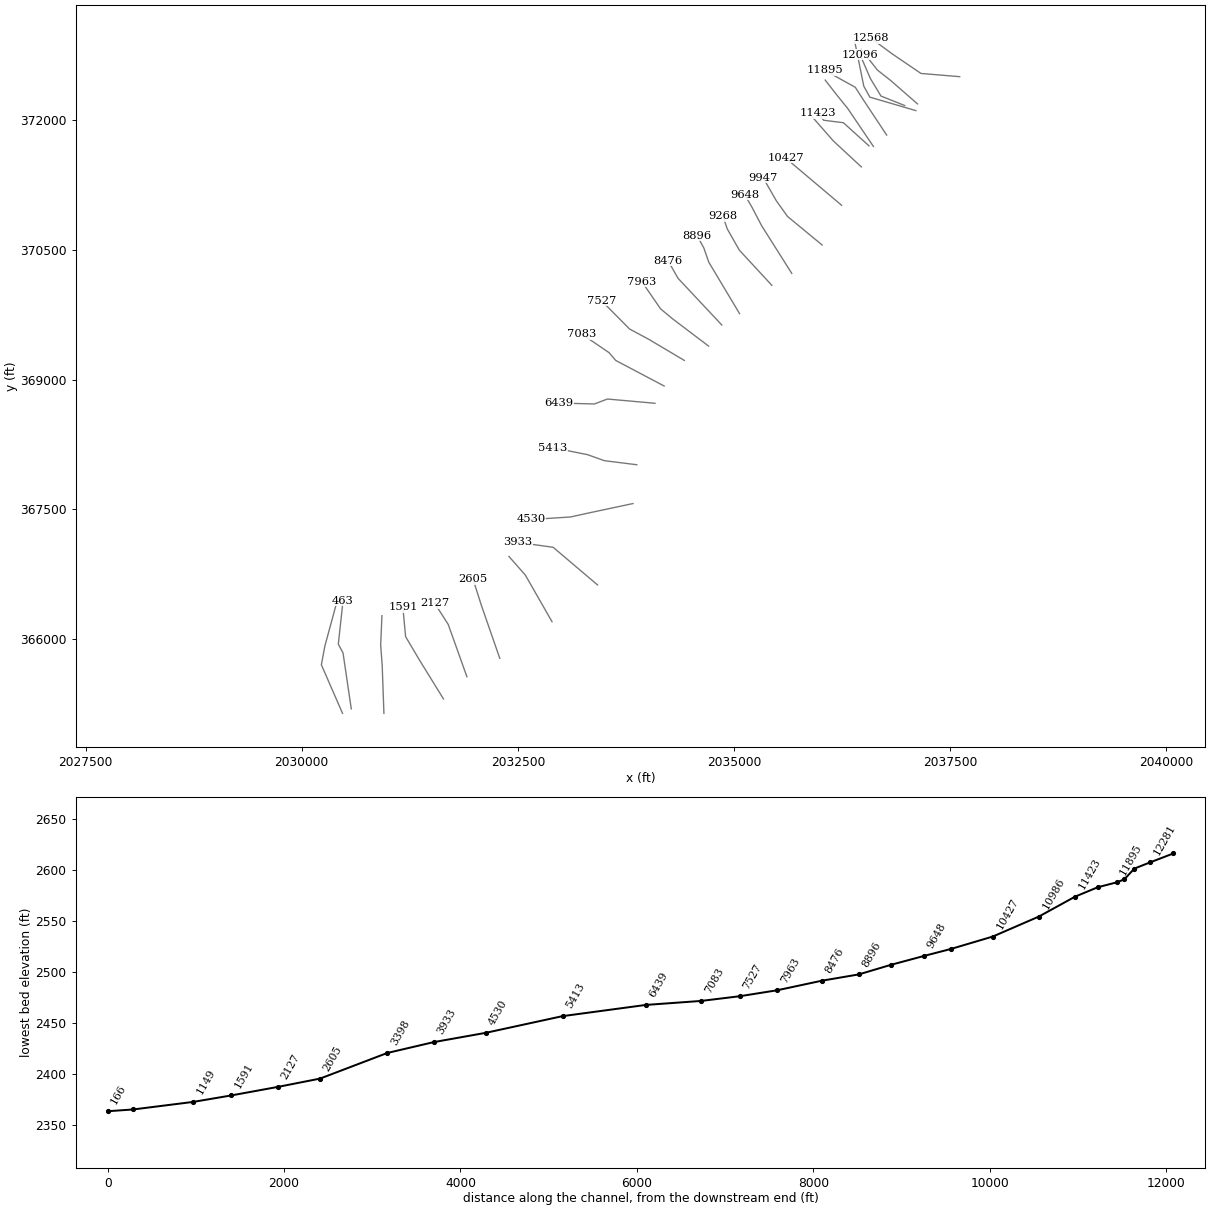
HEC-RAS study MEADOWCK2.prj: MEADOWCK2

--- MEADOWCK2.g01 (geometry) --- (continued)

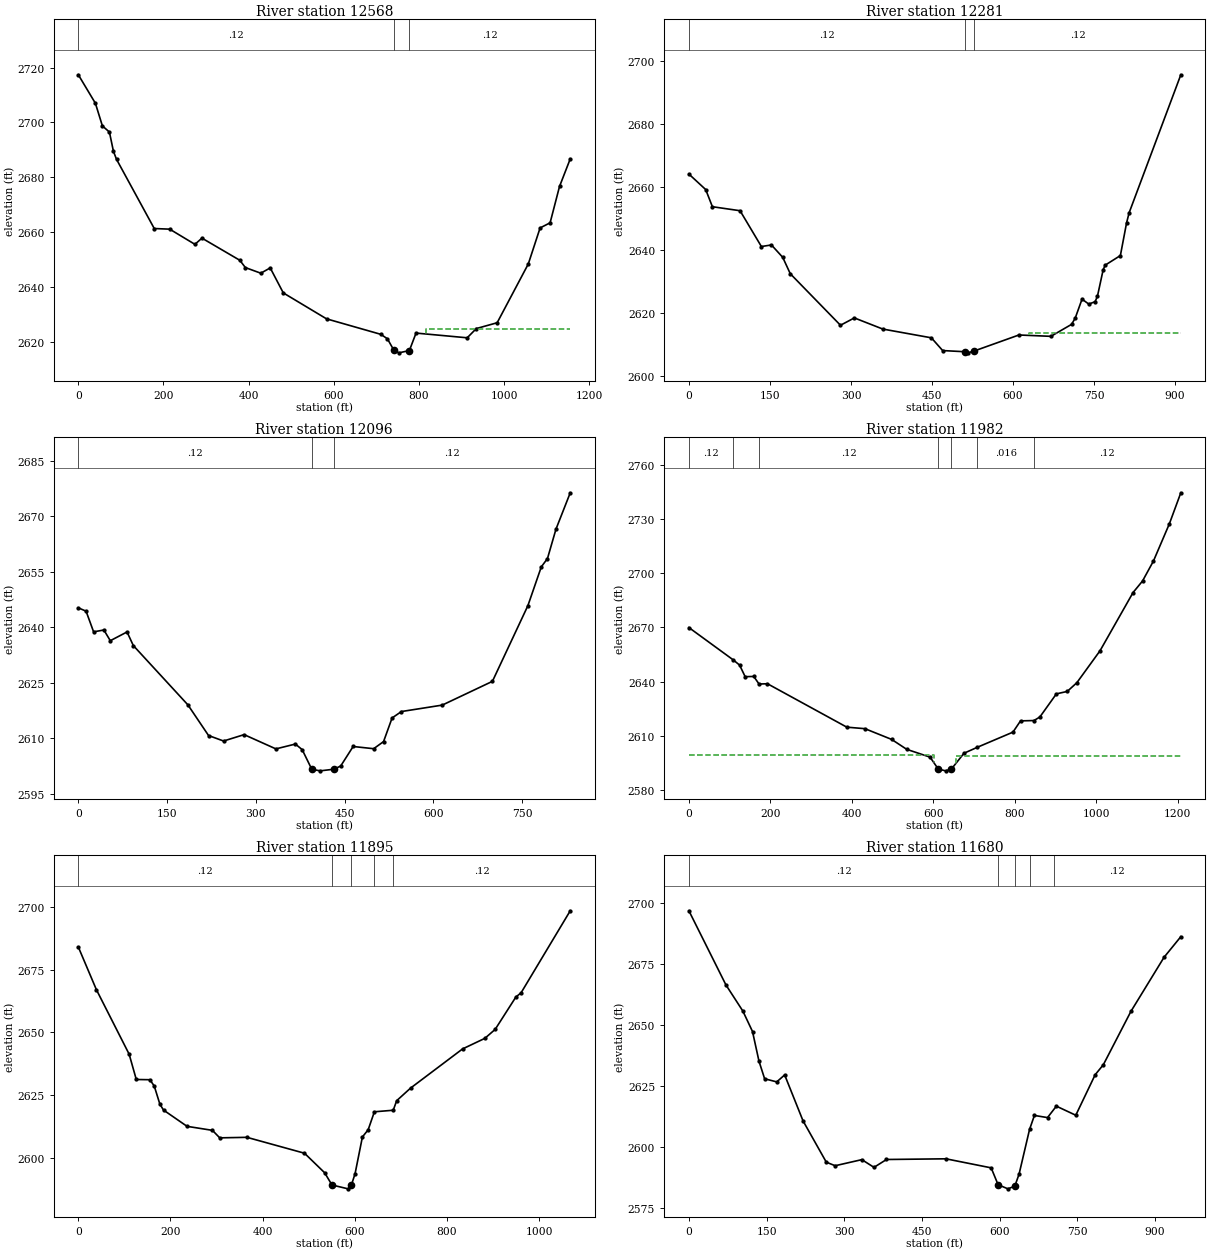
Type RM Length L Ch R = 1 ,12568   ,264.7,264.7,264.7
XS GIS Cut Line= 4
 2037610.9073733372505.2456738522037162.72102276372542.594536397
2036826.58125985372771.3563194892036586.14795721 372948.76341658
#Sta/Elev= 30
       0 2717.35    40.1 2706.96    56.5 2698.72      73 2696.48    82.5 2689.43
    89.7 2686.54   178.3 2661.32   214.6 2661.09   273.8 2655.56   290.3 2657.82
   379.2 2649.75   392.3 2647.09   428.5 2645.04   450.6 2646.97   481.3 2637.86
   582.8 2628.41   710.4 2622.76   725.8 2621.14   741.1 2616.93   752.9 2616.02
   777.4 2616.86     793 2623.22   913.1  2621.5   934.6 2624.87   983.5 2626.99
  1056.6 2648.41  1084.3 2661.54  1107.8  2663.4  1129.9 2676.64  1155.1 2686.71
#Mann= 3 ,-1 , 0
       0     .12       0   741.1     .04       0   777.4     .12       0
#XS Ineff= 2 , 0
                          815.22         2624.64
Permanent Ineff=
       F       F
Bank Sta=741.1,777.4
XS Rating Curve= 0 ,0
Exp/Cntr(USF)=0,0
Exp/Cntr=0.3,0.1

Type RM Length L Ch R = 1 ,12281   ,178.7,178.7,178.7
XS GIS Cut Line= 4
 2037123.0378563372190.1146461242036812.57543639372460.893899579
2036658.51137839372582.2777028522036471.76706567 372820.37670158
#Sta/Elev= 30
       0 2664.01    31.1 2659.09    43.5 2653.64    94.7 2652.37   134.2    2641
   152.8  2641.5   173.7 2637.57   187.7 2632.36   280.6    2616   306.3 2618.33
     359 2614.79   448.9 2612.01   469.8 2607.96   511.1 2607.59   516.4 2607.24
   528.2 2607.83     611 2612.91   670.2 2612.48   708.5 2616.29   715.3 2618.31
   727.8 2624.29   740.3 2622.72     752 2623.48   756.3 2625.18   766.9  2633.6
   770.7 2635.09   798.8 2638.13   810.4 2648.62   815.1 2651.76   910.7 2695.54
#Mann= 3 ,-1 , 0
       0     .12       0   511.1     .04       0   528.2     .12       0
#XS Ineff= 2 , 0
                          630.43         2613.63
Permanent Ineff=
       F       F
Bank Sta=511.1,528.2
XS Rating Curve= 0 ,0
Exp/Cntr(USF)=0,0
Exp/Cntr=0.3,0.1

Type RM Length L Ch R = 1 ,12096   ,114.2,114.2,114.2
XS GIS Cut Line= 4
2036974.85729844 372171.621613322036700.20067889372281.037665011
2036577.38674332372484.2389038662036459.03876904372757.779033094
#Sta/Elev= 30
       0 2645.27    13.1 2644.36    25.8 2638.77    43.2 2639.27      54 2636.37
    82.3 2638.74    92.9 2635.06   185.1 2619.01     220 2610.71   245.4 2609.22
   280.1 2610.95   333.8 2607.09   366.7  2608.4   378.2 2606.89   394.5 2601.55
   408.8 2601.15   431.8 2601.59   443.3 2602.46   464.3 2607.74     499 2607.14
   515.7 2609.07   530.1 2615.46   545.9  2617.2   614.8 2618.94   699.6 2625.37
   759.5 2645.84   782.2 2656.36   792.6  2658.6     807 2666.57   831.1 2676.41
#Mann= 3 ,-1 , 0
       0     .12       0   394.5     .04       0   431.8     .12       0
Bank Sta=394.5,431.8
XS Rating Curve= 0 ,0
Exp/Cntr(USF)=0,0
Exp/Cntr=0.5,0.3

Type RM Length L Ch R = 1 ,11982   ,87,87,87
XS GIS Cut Line= 4
     2037103.203      372112.876     2036571.372      372268.533
     2036501.326      372395.654     2036400.148      372893.759
#Sta/Elev= 30
       0 2669.89     109 2651.96   124.5 2649.09   138.1 2642.69   159.2 2642.83
   172.2 2638.63   192.9 2638.78   387.7 2614.74   432.2  2613.9   497.7 2607.96
   534.7 2602.47     592 2598.15   612.2 2591.53   630.3 2590.56   644.4 2591.55
   675.3  2600.3     708  2603.6   795.5 2611.99   814.1 2618.22   847.1 2618.41
   861.6 2620.38   902.1 2633.18   928.8 2634.53   952.4 2639.36  1009.3 2657.06
  1090.4  2689.3  1113.6 2695.67  1140.5 2706.78  1179.5 2727.35  1207.6 2744.52
#Mann= 7 ,-1 , 0
       0     .12       0     109    .016       0   172.2     .12       0
   612.2     .04       0   644.4     .12       0     708    .016       0
   847.1     .12       0
#XS Ineff= 2 , 0
          602.22 2599.51  654.76         2598.68
Permanent Ineff=
       F       F
Bank Sta=612.2,644.4
XS Rating Curve= 0 ,0
Exp/Cntr=0.5,0.3

Type RM Length L Ch R = 1 ,11895   ,215.1,215.1,215.1
XS GIS Cut Line= 4
     2036765.944      371830.097     2036496.137      372237.402
     2036402.742      372382.683     2036047.323      372579.849
#Sta/Elev= 30
       0 2684.08    39.3 2667.04   110.3 2641.35   125.8 2631.26   155.3 2631.17
   164.8 2628.65     177 2621.43   184.9 2619.07     236 2612.58   291.1 2610.98
   306.9 2607.99   365.9  2608.2   490.9 2601.86   534.7 2594.06   550.52589.204
   585.4 2587.66   592.82589.204   600.7 2593.73   616.6 2608.35   629.1 2611.22
   642.6 2618.38   683.5    2619     691 2622.81     721 2627.81     834 2643.45
   882.3 2647.66   904.8 2651.25   949.6 2664.12   961.1 2665.86  1067.7 2698.53
#Mann= 5 ,-1 , 0
       0     .12       0   550.5     .04       0   592.8     .12       0
   642.6    .016       0   683.5     .12       0
Bank Sta=550.5,592.8
XS Rating Curve= 0 ,0
Exp/Cntr=0.5,0.3

Type RM Length L Ch R = 1 ,11680   ,255.1,255.1,255.1
XS GIS Cut Line= 4
      2036612.88      371697.788     2036314.536      372138.819
     2036192.604      372289.288     2036055.106        372465.7
#Sta/Elev= 30
       0 2696.64    71.5  2666.3   104.2 2655.59   122.8 2647.23   135.3  2635.1
   146.2 2627.89   169.6 2626.61   184.9 2629.46   220.4 2610.65   265.3 2593.75
   282.4  2592.3   333.9 2594.79   357.4 2591.63   381.5 2594.85   496.3 2595.13
   583.6 2591.43     5972584.531     616 2582.84   629.3 2583.96   637.5 2588.86
   657.7 2607.13   667.1 2612.88   692.4    2612   709.5 2616.68     747 2612.96
   784.4 2629.53   800.2 2633.63   853.5 2655.48   917.5 2677.63   949.8 2686.04
#Mann= 5 ,-1 , 0
       0     .12       0     597     .04       0   629.3     .12       0
  657.79    .016       0  704.71     .12       0
Bank Sta=597,629.3
XS Rating Curve= 0 ,0
Exp/Cntr=0.3,0.1

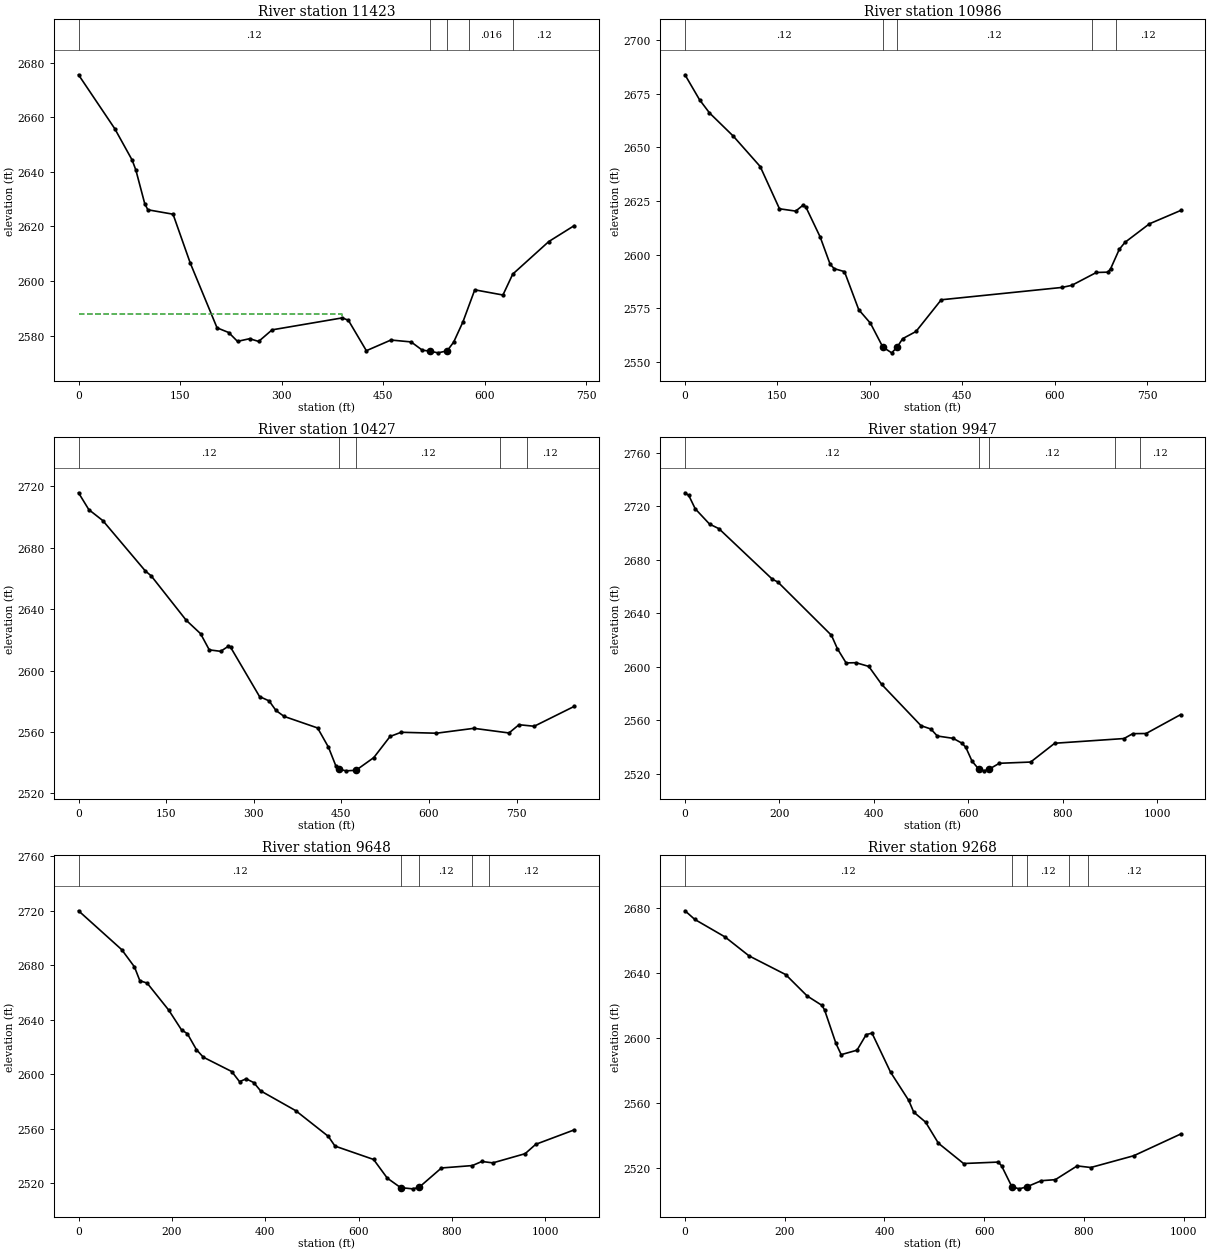
Type RM Length L Ch R = 1 ,11423   ,411.1,411.1,411.1
XS GIS Cut Line= 4
     2036560.994      371705.571     2036265.244      371972.783
     2036036.946      372001.321     2035972.089      372081.744
#Sta/Elev= 30
       0 2675.54    53.5 2655.81    79.2  2644.3    84.7 2640.63    97.8 2628.34
   102.4 2626.09   139.6 2624.47   165.1 2606.53   204.6 2582.85   221.8 2581.13
   234.8 2577.89   252.7 2578.87     266 2577.87   285.9 2582.11   389.8  2586.5
   398.6 2585.59   425.1 2574.47   461.4 2578.38   491.2 2577.69   507.7 2574.67
   518.52574.322   530.9 2573.69   544.42574.414     554  2577.6   567.6 2584.95
   585.2 2596.77   626.8 2594.87   641.3 2602.53   694.5 2614.45     732 2620.27
#Mann= 5 ,-1 , 0
       0     .12       0   518.5     .04       0   544.4     .12       0
  577.26    .016       0  641.52     .12       0
#XS Ineff= 2 , 0
          388.39 2587.84
Permanent Ineff=
       F       F
Bank Sta=518.5,544.4
XS Rating Curve= 0 ,0
Exp/Cntr=0.3,0.1

Type RM Length L Ch R = 1 ,10986   ,522,522,522
XS GIS Cut Line= 3
     2036472.788      371461.707     2036148.501      371762.645
     2035909.826      372035.047
#Sta/Elev= 30
       0 2683.93    23.6  2672.3    39.8 2666.13    78.4 2655.31   122.1 2641.12
   153.4  2621.4   179.7 2620.32   191.6 2623.06   196.2 2622.25   219.5 2608.22
   235.7 2595.45   242.4 2593.45   258.9 2592.08   282.1  2574.3   301.1 2567.98
   321.2 2556.86   335.5 2554.18   344.12556.709   353.3 2560.78     375 2564.14
     416 2578.94     612  2584.7   627.9 2585.68   667.8 2591.68   686.4 2591.83
   691.1 2593.52     705 2602.48   714.3 2605.75   753.9 2614.38   804.6  2620.6
#Mann= 5 ,-1 , 0
       0     .12       0   321.2     .04       0   344.1     .12       0
  660.23    .016       0   699.5     .12       0
Bank Sta=321.2,344.1
XS Rating Curve= 0 ,0
Exp/Cntr=0.3,0.1

Type RM Length L Ch R = 1 ,10427   ,477.3,477.3,477.3
XS GIS Cut Line= 2
      2036244.49      371018.082     2035595.915      371565.479
#Sta/Elev= 30
       0  2715.9    17.7 2704.89    41.6 2697.77   114.3 2664.98   124.5 2661.72
   184.3 2632.83     209 2624.03   223.9 2613.48   243.4 2612.53   256.2 2615.74
   260.5 2615.13     310 2583.03   326.3 2580.22   338.1 2573.97   351.9 2570.12
   409.4 2562.56     428 2550.01   440.8 2537.68   445.62535.737     458 2534.61
   475.12534.956   505.6 2543.25   533.5 2557.03   552.5 2559.75   612.8 2559.14
     677 2562.33   737.1  2559.3   754.2 2564.68   780.3 2563.68   848.7 2576.62
#Mann= 5 ,-1 , 0
       0     .12       0   445.6     .04       0   475.1     .12       0
  721.46    .016       0  767.26     .12       0
Bank Sta=445.6,475.1
XS Rating Curve= 0 ,0
Exp/Cntr=0.3,0.1

Type RM Length L Ch R = 1 ,9947    ,299.3,299.3,299.3
XS GIS Cut Line= 4
     2036018.786      370558.891     2035619.264      370888.367
     2035489.549      371069.968     2035336.486       371337.18
#Sta/Elev= 30
       0 2730.08       8  2728.1    21.7 2718.12      52 2706.69    71.8 2703.28
   184.9 2665.52   196.5 2663.45     310 2623.62   322.7 2613.51     341    2603
     362 2603.15     389 2600.38   416.3 2586.95   499.5 2556.13   520.5 2553.61
     534 2548.41   567.5 2546.67   586.5 2542.98   594.5 2539.83   607.5 2529.64
   621.42523.786   633.4 2522.39     644  2523.7   665.3 2528.03   731.6 2528.96
   782.5    2543   929.1 2546.51   947.7 2550.16   975.9 2550.27    1049 2564.39
#Mann= 5 ,-1 , 0
       0     .12       0   621.4     .04       0     644     .12       0
  911.13    .016       0   963.3     .12       0
Bank Sta=621.4,644
XS Rating Curve= 0 ,0
Exp/Cntr=0.3,0.1

Type RM Length L Ch R = 1 ,9648    ,375.8,375.8,375.8
XS GIS Cut Line= 4
     2035668.556      370229.415      2035320.92      370779.406
     2035206.771      370997.327     2035123.753      371140.014
#Sta/Elev= 30
       0 2719.99    92.6 2691.42   119.8 2678.78   131.4 2668.59     147 2666.86
   193.5 2646.89   220.7 2632.45   233.1 2629.73   252.6 2617.97   267.3 2612.43
   328.2 2601.89   344.9 2594.45   359.1 2596.52   375.4 2593.76     390 2587.71
   465.2 2573.15   535.1 2554.25   549.4 2547.11   632.1 2537.28   661.4 2523.56
     6902516.587   715.6  2515.7   729.42516.769   777.4 2531.03   843.6 2532.79
     864 2535.81   887.4 2534.77   956.6 2541.52   979.4 2548.41  1061.7    2559
#Mann= 5 ,-1 , 0
       0     .12       0     690     .04       0   729.4     .12       0
  843.61    .016       0  878.54     .12       0
Bank Sta=690,729.4
XS Rating Curve= 0 ,0
Exp/Cntr=0.3,0.1

Type RM Length L Ch R = 1 ,9268    ,367.6,367.6,367.6
XS GIS Cut Line= 4
     2035437.663      370091.917      2035061.49      370499.222
     2034921.398       370745.68     2034872.106      370893.555
#Sta/Elev= 30
       0  2678.2    19.8 2672.85    80.2 2662.11   128.5 2650.42   201.9 2638.91
     245 2625.74   274.5 2619.98   279.9 2617.14   302.7 2596.52   313.2 2589.61
   344.9 2592.35   363.4 2601.97     375 2602.85   412.2 2578.81   448.6 2561.43
   458.6 2554.24   482.4 2548.07   508.1 2535.08   558.6 2522.57   628.2 2523.46
   634.8 2521.14   655.42508.298     670 2506.98   684.82508.155   714.5 2511.99
   742.6 2512.63   786.3  2521.1   813.7 2520.12   899.9 2527.37   993.8 2540.72
#Mann= 5 ,-1 , 0
       0     .12       0   655.4     .04       0   684.8     .12       0
  769.18    .016       0  808.36     .12       0
Bank Sta=655.4,684.8
XS Rating Curve= 0 ,0
Exp/Cntr=0.3,0.1

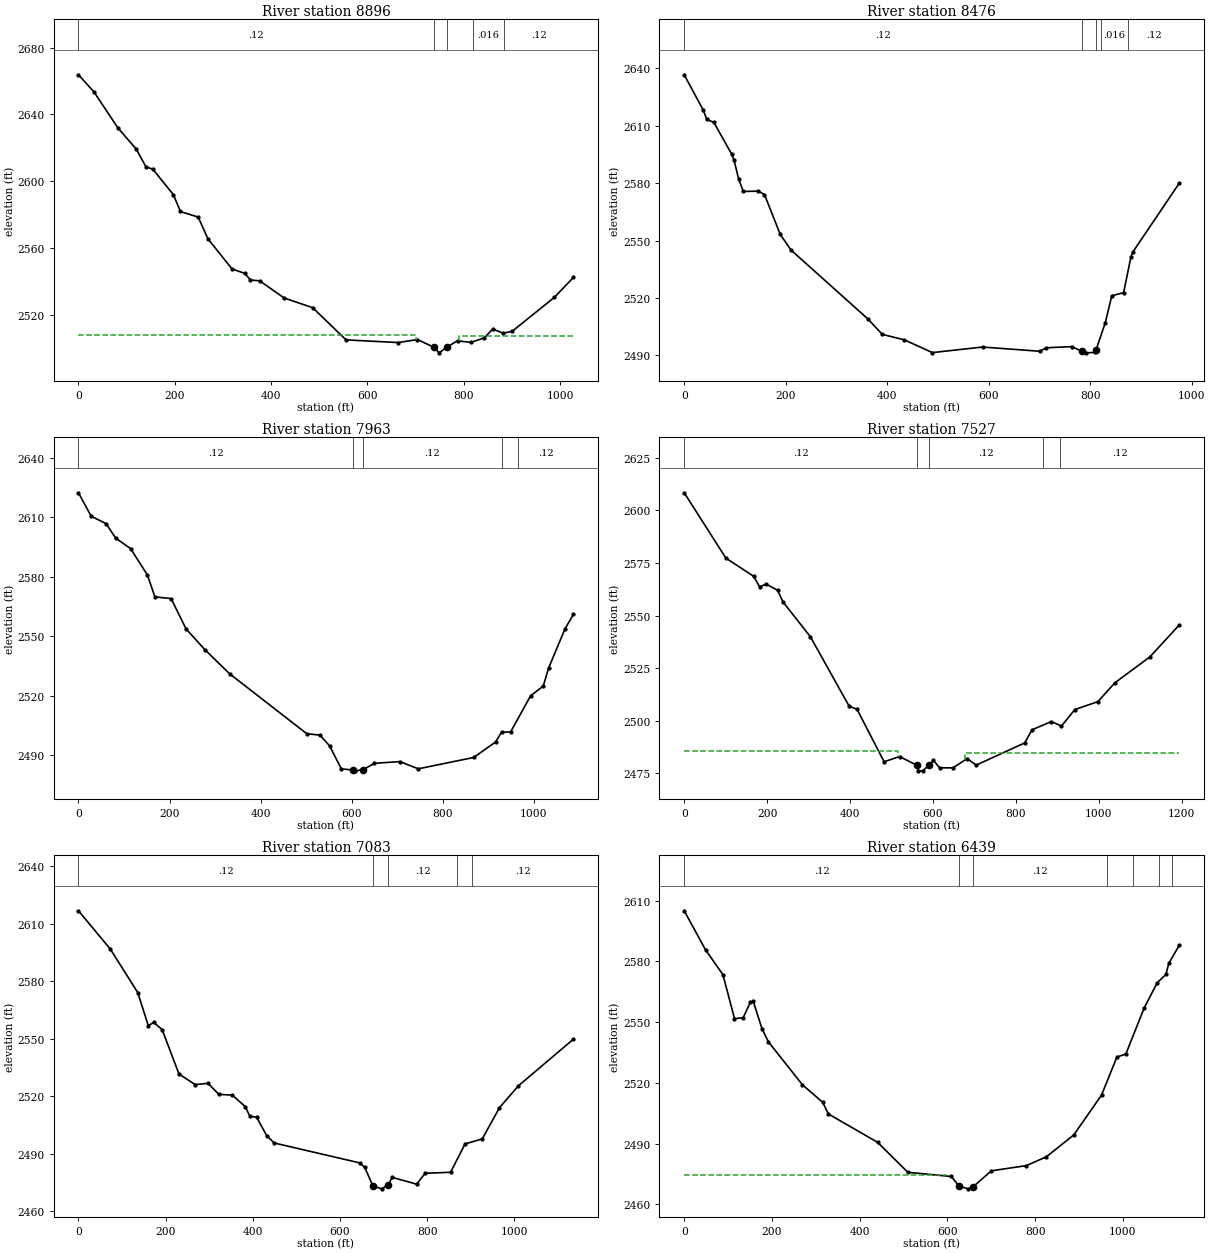
Type RM Length L Ch R = 1 ,8896    ,419.1,419.1,419.1
XS GIS Cut Line= 4
     2035064.084      369765.036     2034708.665       370359.13
     2034651.591      370522.571     2034573.762      370665.257
#Sta/Elev= 30
       0  2663.7    31.8 2653.61    81.8 2631.99   120.1 2619.24   139.9 2608.78
   154.5 2607.26   196.9 2592.11   211.8    2582   248.6 2578.64   268.6 2565.79
   318.9 2547.62   345.2 2545.02   357.1 2541.07   376.4 2540.55   427.5 2530.25
   486.3 2524.53   555.7 2505.26   663.9 2503.68   703.9 2505.48     7382500.875
     749 2497.53   764.62500.896   787.1 2504.73   815.1 2503.77   842.9  2506.5
   860.2 2511.78   881.6 2509.26   900.8 2510.42     988 2530.63  1027.9 2542.62
#Mann= 5 ,-1 , 0
       0     .12       0     738     .04       0   764.6     .12       0
  819.42    .016       0  883.24     .12       0
#XS Ineff= 2 , 0
          700.07 2507.97  790.46         2507.52
Permanent Ineff=
       F       F
Bank Sta=738,764.6
XS Rating Curve= 0 ,0
Exp/Cntr=0.3,0.1

Type RM Length L Ch R = 1 ,8476    ,504.7,504.7,504.7
XS GIS Cut Line= 3
     2034859.135      369632.726     2034353.247       370172.34
     2034236.503       370377.29
#Sta/Elev= 30
       0  2636.6    37.5 2618.12    44.5 2613.26    58.4 2611.72    93.2 2595.31
    97.9 2592.31   107.1 2582.35   116.4 2575.63     146 2575.83   158.2 2574.05
   189.1  2553.3   210.2 2545.11   362.5 2508.93   390.3 2500.99   433.8 2498.14
     489 2491.48   587.9 2494.38   700.4 2492.18   713.9    2494   763.3 2494.58
   783.8 2492.25   791.4 2491.35   808.6 2491.54   811.72492.914   829.9 2507.15
   842.6 2521.17   865.9 2522.78   880.3 2541.35   884.1 2544.01   975.5 2579.91
#Mann= 5 ,-1 , 0
       0     .12       0   783.8     .04       0   811.7     .12       0
   820.8    .016       0  875.13     .12       0
Bank Sta=783.8,811.7
XS Rating Curve= 0 ,0
Exp/Cntr=0.3,0.1

Type RM Length L Ch R = 1 ,7963    ,422.6,422.6,422.6
XS GIS Cut Line= 4
     2034706.071      369388.862     2034288.389      369705.367
     2034150.891      369819.516      2033932.97       370136.02
#Sta/Elev= 30
       0 2622.22    27.9  2610.4    60.8 2606.64    81.4 2599.42   114.4 2594.09
   151.4 2580.77   167.8 2569.72   203.4 2568.89   236.1 2553.66   277.4 2543.15
   332.2  2530.9   501.3 2500.75   530.3 2500.03   551.6 2494.59   577.2 2483.01
     6022482.477     607 2482.03   624.7 2482.54   649.7 2485.83     706 2486.69
   746.1 2483.05     868 2488.77   915.9 2496.58     929 2501.51   948.9  2501.6
   992.7 2519.82  1020.6 2524.77  1032.6 2533.98  1068.4  2553.6    1087 2560.98
#Mann= 5 ,-1 , 0
       0     .12       0     602     .04       0   624.7     .12       0
  929.83    .016       0  965.69     .12       0
Bank Sta=602,624.7
XS Rating Curve= 0 ,0
Exp/Cntr=0.3,0.1

Type RM Length L Ch R = 1 ,7527    ,438.6,438.6,438.6
XS GIS Cut Line= 4
     2034425.887      369222.827     2034010.799      369469.286
     2033792.878      369586.029     2033465.997      369915.505
#Sta/Elev= 30
       0 2608.39   100.6 2577.32   167.7 2568.66   182.1 2563.61   197.1    2565
   225.2 2562.09     238 2556.58   304.2    2540   398.2 2506.83   416.7 2505.56
   482.2 2480.52   519.4 2483.01   560.82478.898   564.1 2476.27   575.2 2476.21
   590.1 2478.83   601.3 2481.14   616.2 2477.62   648.5 2477.65   682.5 2482.04
   704.3 2478.92   821.4 2489.49   839.1 2495.73   885.7 2499.63   910.1 2497.49
   942.4 2505.35   997.9 2509.11  1039.4 2518.15  1123.3 2530.35  1194.1 2545.52
#Mann= 5 ,-1 , 0
       0     .12       0   560.8     .04       0   590.1     .12       0
  864.64    .016       0  906.25     .12       0
#XS Ineff= 2 , 0
          515.61 2485.84  677.74         2484.68
Permanent Ineff=
       F       F
Bank Sta=560.8,590.1
XS Rating Curve= 0 ,0
Exp/Cntr=0.3,0.1

Type RM Length L Ch R = 1 ,7083    ,627.3,627.3,627.3
XS GIS Cut Line= 4
       2034192.4      368927.077     2033632.032      369222.827
     2033554.203      369313.628     2033237.698      369528.954
#Sta/Elev= 30
       0 2616.74    72.9  2596.8     136 2574.06   160.3 2556.69   172.5  2558.5
   191.9 2554.73   230.7  2531.5   267.9 2526.01   297.5 2526.66     322  2520.9
   353.2 2520.51   382.9 2514.46   393.4 2509.41   408.8    2509   432.3 2499.23
   449.3 2495.51   645.2 2485.14   657.1 2482.78   675.62473.067   696.6 2471.58
   711.22473.792   719.9 2477.56   776.1 2474.02   795.6 2479.71     854 2480.22
   887.1 2495.02   926.6 2497.64   966.2 2513.97  1009.8  2525.4    1136 2549.73
#Mann= 5 ,-1 , 0
       0     .12       0   675.6     .04       0   711.2     .12       0
  868.16    .016       0  903.88     .12       0
Bank Sta=675.6,711.2
XS Rating Curve= 0 ,0
Exp/Cntr=0.3,0.1

Type RM Length L Ch R = 1 ,6439    ,945.1,945.1,945.1
XS GIS Cut Line= 4
     2034086.034      368727.316     2033536.043      368776.608
     2033385.573      368719.533     2032970.486      368729.911
#Sta/Elev= 30
       0 2604.96    48.7 2585.65    88.2 2573.45   114.6 2551.72   134.3 2552.11
   150.8 2559.81   157.4 2560.28   177.2 2546.73   191.9 2540.25   269.4 2519.07
   315.5 2510.42   328.7 2504.63   440.7 2490.64   509.9 2475.82   608.9 2473.76
   626.22469.037   647.3 2467.66   658.42468.673   700.1 2476.55   779.7 2479.12
   825.6 2483.49     888 2494.29   951.2 2513.93   986.4 2532.77  1006.7 2534.23
  1048.8 2557.16  1078.3 2569.44    1098 2573.53  1104.6 2579.01  1128.3 2587.87
#Mann= 7 ,-1 , 0
       0     .12       0   626.2     .04       0   658.4     .12       0
  964.51    .016       0 1023.61     .12       0  1082.7     .08       0
 1112.25     .12       0
#XS Ineff= 2 , 0
          596.09 2474.73
Permanent Ineff=
       F       F
Bank Sta=626.2,658.4
XS Rating Curve= 0 ,0
Exp/Cntr=0.3,0.1

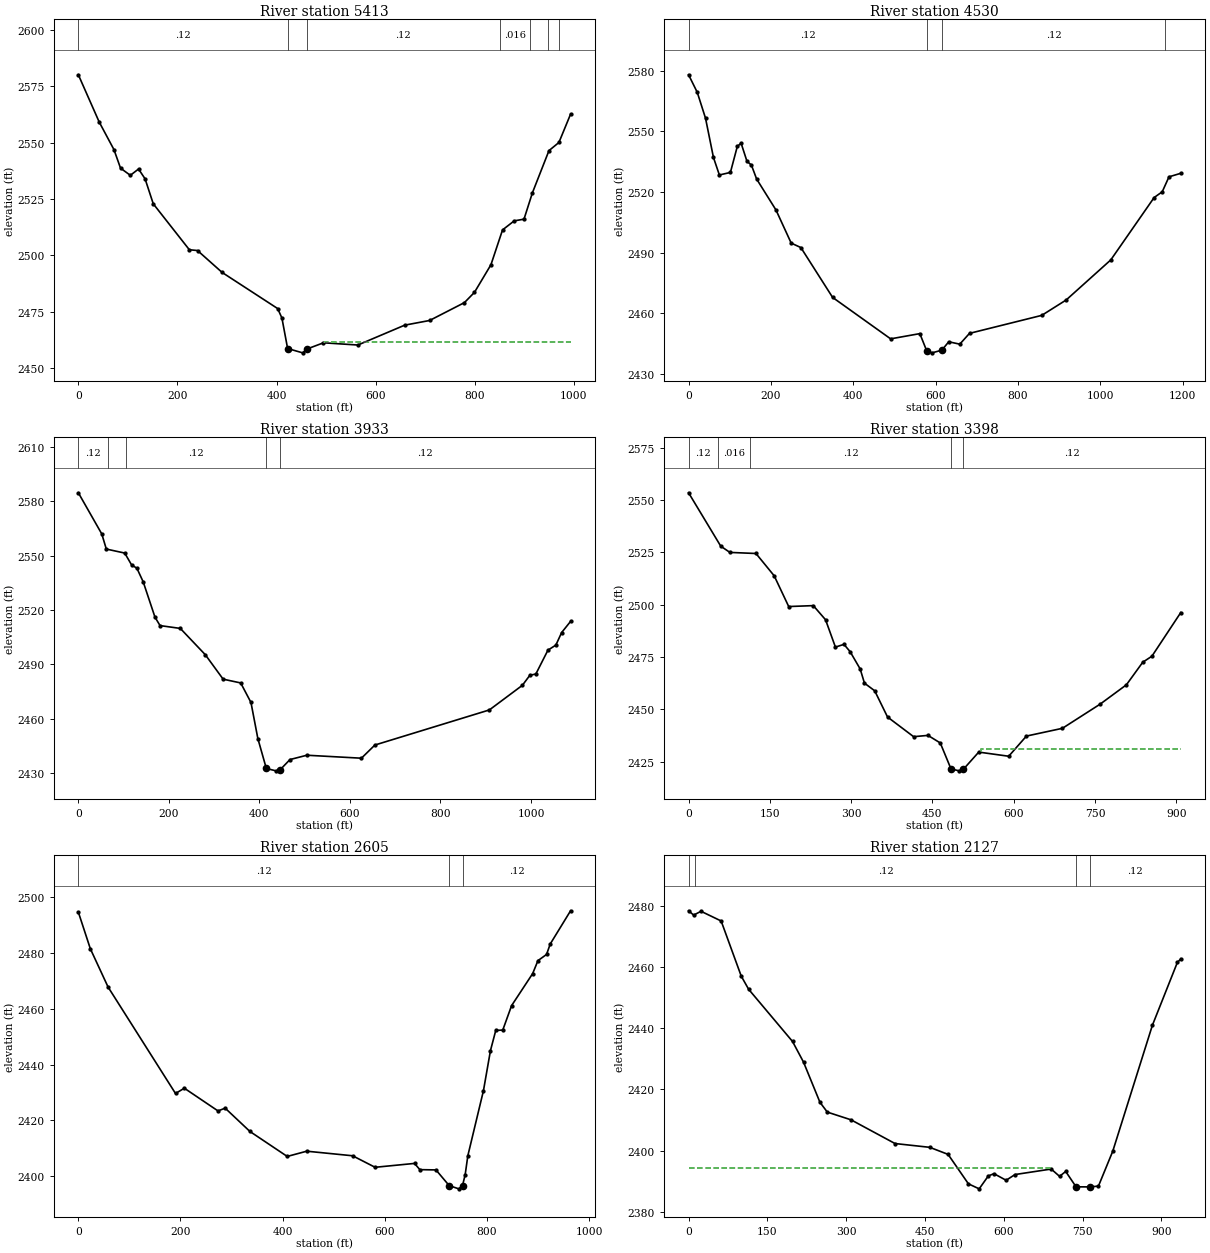
Type RM Length L Ch R = 1 ,5413    ,871.6,871.6,871.6
XS GIS Cut Line= 4
     2033875.896      368016.479     2033502.317      368063.176
      2033305.15      368133.222     2032905.628      368213.645
#Sta/Elev= 30
       0 2580.14    42.1 2559.16    71.9  2546.9    85.1  2538.7   104.9  2535.5
   121.5  2538.3   134.7 2533.93   151.2 2522.85     224 2502.46   240.5 2502.11
   290.1 2492.39   402.2 2476.35   410.8 2472.16   422.3 2458.61   452.6 2456.69
   461.52458.402   494.7 2461.15   564.1 2460.16   658.6 2468.98   708.8 2471.05
   779.1 2478.99   799.4 2483.56   832.6  2495.8     856 2511.26   879.5 2515.28
   899.3 2516.04   916.3 2527.74   949.7 2546.47   969.8 2550.09   993.3 2562.66
#Mann= 7 ,-1 , 0
       0     .12       0   422.3     .04       0   461.5     .12       0
  850.42    .016       0  910.68     .12       0  948.29     .06       0
  970.94     .12       0
#XS Ineff= 2 , 0
                           495.2         2461.51
Permanent Ineff=
       F       F
Bank Sta=422.3,461.5
XS Rating Curve= 0 ,0
Exp/Cntr=0.3,0.1

Type RM Length L Ch R = 1 ,4530    ,589.8,589.8,589.8
XS GIS Cut Line= 4
     2033831.793      367567.665     2033307.744       367456.11
     2033107.983      367412.007     2032653.981       367383.47
#Sta/Elev= 30
       0 2578.09    21.1 2569.39    41.2 2556.54    60.4 2537.14    74.8 2528.44
   101.6 2529.71   118.4 2542.63   127.6 2544.18   141.9 2535.16   152.5  2533.4
   165.3 2526.42   212.3 2511.08   249.2 2494.69   272.7 2492.48   349.8 2467.78
   490.7 2447.25   561.6 2449.84     578 2441.45   591.4 2440.32     6152441.653
   631.8  2445.8   658.6 2444.62   682.2 2449.97   857.6 2458.88   916.9  2466.5
  1025.3 2486.37  1130.5 2517.26  1150.2 2520.11  1166.6 2527.53  1195.3 2529.28
#Mann= 4 ,-1 , 0
       0     .12       0     578     .04       0     615     .12       0
 1157.94    .016       0
Bank Sta=578,615
XS Rating Curve= 0 ,0
Exp/Cntr=0.3,0.1

Type RM Length L Ch R = 1 ,3933    ,526.3,526.3,526.3
XS GIS Cut Line= 3
     2033421.893      366625.935     2032908.222      367061.777
     2032498.323      367118.851
#Sta/Elev= 30
       0 2584.63    51.8 2561.91    61.8 2553.58   102.5 2551.37   117.7 2544.81
   129.3 2543.03   143.3 2535.49   169.3 2516.02   180.5 2511.36   225.3  2509.8
   280.6 2495.26   319.9  2481.8   358.7 2479.72   381.4 2468.94   396.6 2449.04
   415.32432.537   436.6 2431.23   444.7 2431.53   467.6 2437.46   504.9 2439.84
   625.4  2438.2   655.2 2445.47   908.1 2464.83     981 2478.41   997.6 2483.96
  1010.8 2484.65  1037.5 2497.81    1055  2500.6  1067.8 2507.54  1087.5 2513.67
#Mann= 5 ,-1 , 0
       0     .12       0   66.32    .016       0  106.03     .12       0
   415.3     .04       0   444.7     .12       0
Bank Sta=415.3,444.7
XS Rating Curve= 0 ,0
Exp/Cntr=0.3,0.1

Type RM Length L Ch R = 1 ,3398    ,762.8,762.8,762.8
XS GIS Cut Line= 3
     2032895.251       366200.47     2032586.529      366740.084
     2032397.146      366955.411
#Sta/Elev= 30
       0 2553.54    59.4 2528.01    76.3 2525.03   124.4 2524.51     158 2513.85
   184.8 2499.15   230.2 2499.59   252.8 2492.83     271 2479.76   286.8 2481.07
   298.2 2477.55   316.7  2469.3   324.6 2462.52   343.5 2458.87   367.2 2446.33
   415.3 2436.93   441.8 2437.55   464.5 2433.93   484.32421.516   499.4  2420.6
   507.22421.354   535.5 2429.56   590.8 2427.58   623.5 2437.22   689.9 2440.93
   759.5 2452.48     808 2461.73   838.2 2472.53   855.1 2475.41   908.4  2496.3
#Mann= 5 ,-1 , 0
       0     .12       0   53.96    .016       0  113.44     .12       0
   484.3     .04       0   507.2     .12       0
#XS Ineff= 2 , 0
                          540.22         2431.15
Permanent Ineff=
       F       F
Bank Sta=484.3,507.2
XS Rating Curve= 0 ,0
Exp/Cntr=0.3,0.1

Type RM Length L Ch R = 1 ,2605    ,472.1,472.1,472.1
XS GIS Cut Line= 3
     2032290.779      365777.599     2032078.047      366389.853
     2031982.058      366690.792
#Sta/Elev= 30
       0 2494.66    23.5 2481.53    58.3 2467.79   190.3 2429.67   207.6 2431.56
   273.6 2423.41   287.5 2424.42   336.1 2416.05   409.1 2407.11   447.3 2408.99
   537.1 2407.35   581.2 2403.22   658.4 2404.61   668.8 2402.38   700.4 2402.28
   726.32396.652   745.1  2395.5   752.4 2396.68   757.6 2400.58   762.8 2407.36
   793.4  2430.7   807.1 2445.04   817.5 2452.27   831.2 2452.39   848.5 2461.16
   889.8 2472.65   900.1 2477.28   916.9 2479.48   924.2 2483.25     964 2495.14
#Mann= 3 ,-1 , 0
       0     .12       0   726.3     .04       0   752.4     .12       0
Bank Sta=726.3,752.4
XS Rating Curve= 0 ,0
Exp/Cntr=0.3,0.1

Type RM Length L Ch R = 1 ,2127    ,535.8,535.8,535.8
XS GIS Cut Line= 3
     2031910.571       365564.29     2031694.379      366169.626
     2031535.839      366417.526
#Sta/Elev= 30
       0  2478.5     9.7 2477.09    23.7 2478.33      62 2475.16   100.3 2457.09
   114.3 2452.81   197.9 2435.71   218.8 2428.96   250.1  2415.8   264.1 2412.59
   309.3 2410.06     393  2402.3   459.1 2401.06     494 2398.75   532.7 2389.11
   553.2 2387.47   570.6  2391.7   581.4 2392.43   604.5 2390.27   621.4 2392.15
   690.3 2393.95   706.2 2391.56   717.9 2393.16   737.6 2388.13   763.82388.104
   780.2 2388.36   807.5  2399.8   882.9 2441.01   930.4 2461.57     937 2462.76
#Mann= 4 ,-1 , 0
       0     .08       0   12.39     .12       0   737.6     .04       0
   763.8     .12       0
#XS Ineff= 2 , 0
           688.2 2394.15
Permanent Ineff=
       F       F
Bank Sta=737.6,763.8
XS Rating Curve= 0 ,0
Exp/Cntr=0.3,0.1

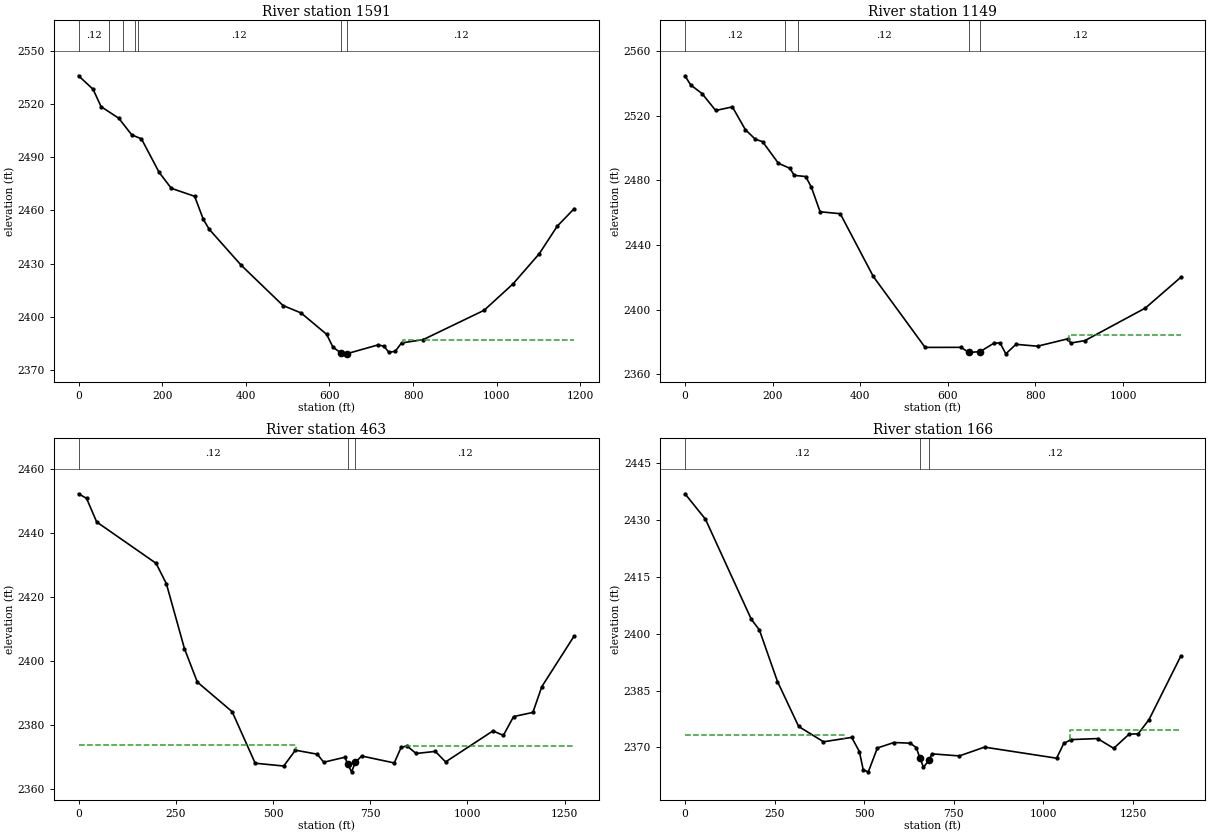
Type RM Length L Ch R = 1 ,1591    ,432.2,432.2,432.2
XS GIS Cut Line= 4
     2031639.611      365307.743     2031360.003      365760.304
     2031201.462      366028.381     2031169.754      366368.523
#Sta/Elev= 30
       0 2536.09    34.7 2528.51      54 2518.65    96.4 2512.07   127.2 2502.72
   150.4 2500.48   192.8  2481.5   221.9 2472.51   277.6 2468.01   298.2 2455.07
   312.3 2449.42   388.8 2429.09   488.9  2406.3     532 2402.11   593.1 2390.04
   608.4 2382.76   627.72379.437   634.8    2379   642.7 2379.15   716.3 2384.05
   730.4 2383.27   741.8 2379.92     757 2380.37   772.3 2385.15     824 2387.02
   969.8 2403.62    1039 2418.56  1101.6 2435.57  1144.5 2451.11    1185    2461
#Mann= 7 ,-1 , 0
       0     .12       0   72.23    .016       0  106.95     .12       0
  134.66    .016       0  141.67     .12       0   627.7     .04       0
   642.7     .12       0
#XS Ineff= 2 , 0
                          775.32         2386.75
Permanent Ineff=
       F       F
Bank Sta=627.7,642.7
XS Rating Curve= 0 ,0
Exp/Cntr=0.3,0.1

Type RM Length L Ch R = 1 ,1149    ,679.8,679.8,679.8
XS GIS Cut Line= 4
      2030950.68      365140.555     2030930.502       365699.77
     2030913.207      365927.492      2030927.62      366270.516
#Sta/Elev= 30
       0  2544.8      13 2539.13    39.2 2533.74      70 2523.31   108.2 2525.54
   137.7 2511.48   160.7 2505.48   177.1 2504.01   213.2 2490.64   239.5 2487.51
   249.3 2483.17   275.6 2482.41   288.6 2475.73   308.4 2460.61   354.4 2459.41
   429.9 2420.54   548.1 2376.64   630.3 2376.68   647.72373.497   673.8 2374.05
     706  2379.4   719.2  2379.3   732.4 2372.66   755.4 2378.55   804.7 2377.39
   873.6 2381.94   880.6 2379.33     913 2380.87    1051 2401.05  1131.3 2419.95
#Mann= 5 ,-1 , 0
       0     .12       0  228.78    .016       0  258.34     .12       0
   647.7     .04       0   673.8     .12       0
#XS Ineff= 2 , 0
                          877.04         2384.32
Permanent Ineff=
       F       F
Bank Sta=647.7,673.8
XS Rating Curve= 0 ,0
Exp/Cntr=0.3,0.1

Type RM Length L Ch R = 1 ,463     ,287.3,287.3,287.3
XS GIS Cut Line= 4
     2030573.066      365192.441     2030477.941      365838.133
     2030423.173      365941.905     2030477.941      366443.469
#Sta/Elev= 30
       0 2452.39    20.7 2450.96    46.7 2443.56   199.4 2430.61     226 2424.18
   272.4 2403.89   305.5 2393.41   395.1 2384.12   454.3 2367.98   527.7  2367.1
   557.6 2372.06     614 2370.81   630.5 2368.29   685.1 2369.86   691.82367.786
   702.1 2365.28   711.72368.223   728.1 2370.24   811.9 2368.07   829.4 2372.91
   844.3 2373.42     868 2371.03   917.5 2371.68   943.9 2368.39  1065.6  2378.1
  1092.4  2376.7  1118.8  2382.6  1168.3 2383.89  1191.4 2391.99  1274.5 2407.84
#Mann= 3 ,-1 , 0
       0     .12       0   691.8     .04       0   711.7     .12       0
#XS Ineff= 2 , 0
             560 2373.63  839.68         2373.44
Permanent Ineff=
       F       F
Bank Sta=691.8,711.7
XS Rating Curve= 0 ,0
Exp/Cntr=0.3,0.1

Type RM Length L Ch R = 1 ,166     ,108.6,98.1,87.6
XS GIS Cut Line= 4
     2030472.176      365140.555     2030227.159      365702.653
     2030267.515      365918.844     2030411.643      366449.234
#Sta/Elev= 30
       0 2436.94    57.1 2430.24     185 2403.82   207.5 2401.03     258  2387.4
   317.1 2375.54   386.4 2371.49   465.1 2372.65   486.6 2368.89   497.3 2364.06
   511.5 2363.56   536.7 2369.86   583.2  2371.3   628.6 2371.12   645.3 2369.93
   655.2 2367.23   665.3 2364.81   681.12366.611   688.7 2368.31   765.4 2367.76
   835.6 2370.08  1036.8 2367.16  1056.6 2371.04    1077 2372.07  1150.8 2372.34
    1196 2369.77    1239 2373.51    1264 2373.58  1294.6 2377.36  1382.7 2394.02
#Mann= 3 ,-1 , 0
       0     .12       0   655.2     .04       0   681.1     .12       0
#XS Ineff= 2 , 0
          444.35 2373.31 1074.42         2374.52
Permanent Ineff=
       F       F
Bank Sta=655.2,681.1
XS Rating Curve= 0 ,0
Exp/Cntr=0.3,0.1
LCMann Table=0

Chan Stop Cuts=-1
Use User Specified Reach Order=0
Composite Channel Slope=5